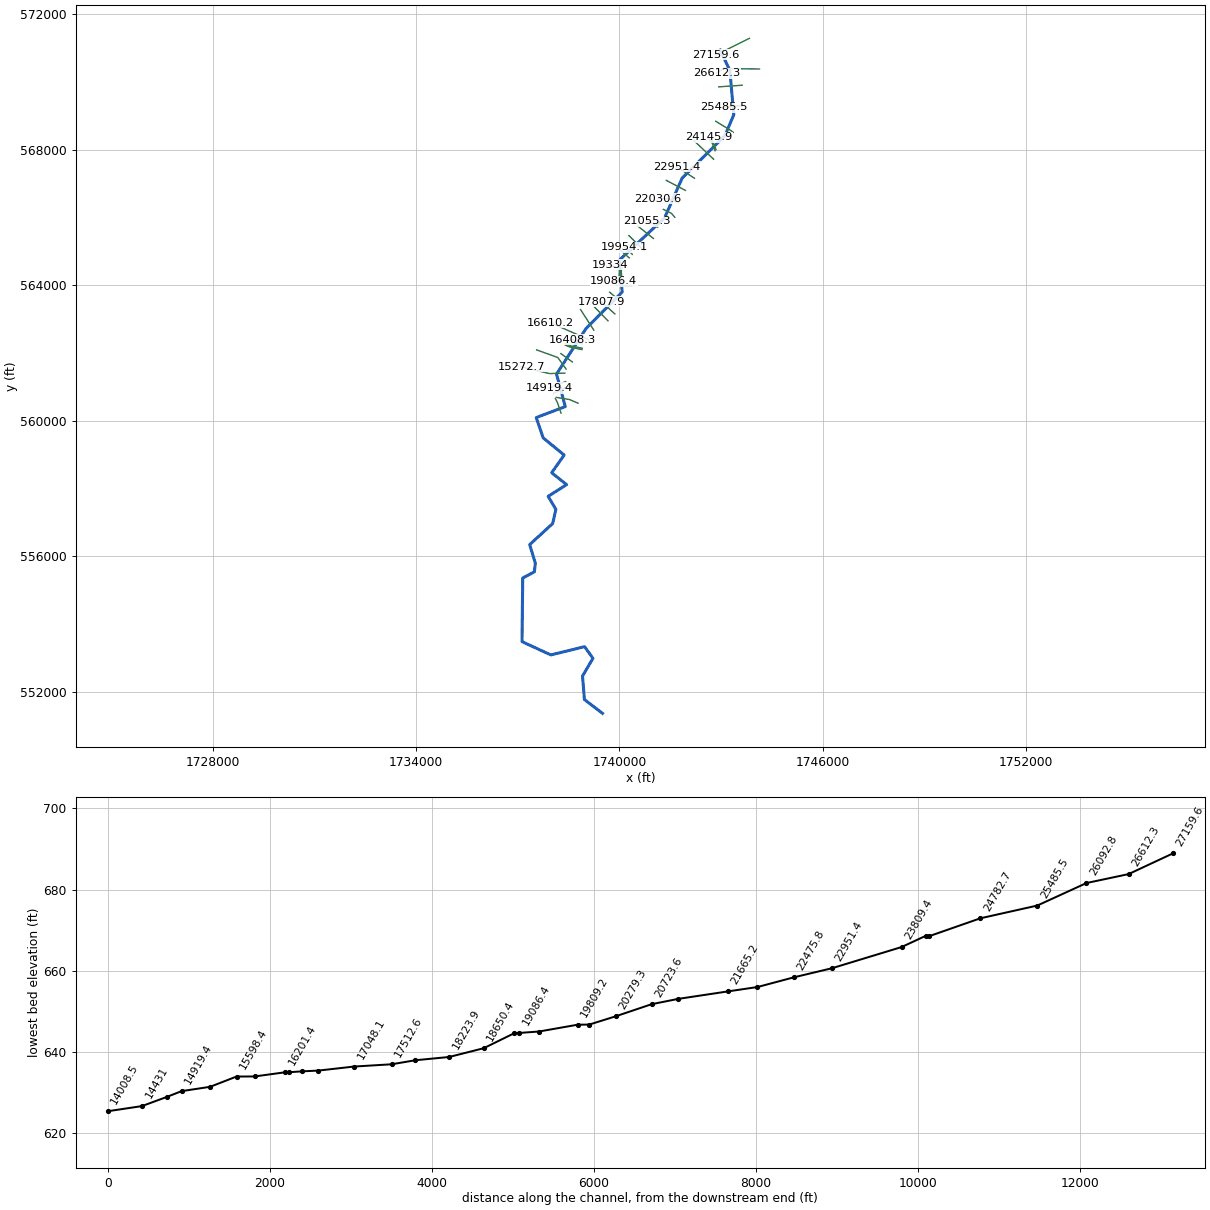
--- ManilaCr.prj (project) ---

Proj Title=ManilaCr
Current Plan=p01
Default Exp/Contr=0,0
English Units
Geom File=g01
Flow File=f01
Plan File=p01
BEGIN DESCRIPTION:
AMEC Environment & Infrastructure, 2013
Projection: NAD 1983 State Plane West Virginia South FIPS 4702 (US Feet)
Vertical Datum: NAVD 1988
END DESCRIPTION:
DSS Export Rating Curves= 0
DSS Export Rating Curve Sorted= 0
DSS Export Volume Flow Curves= 0
DXF OffsetX= 0
DXF OffsetY= 0
DXF ScaleX= 0
DXF ScaleY= 0

--- ManilaCr.p01 (plan) ---

Plan Title=Floodplain
Program Version=4.00
Geom File=g01
Flow File=f01
K Sum by GR=0
Std Step Tol=0.01
Critical Tol=0.01
Num of Std Step Trials=20
Max Error Tol=0.3
Flow Tol Ratio=0.001
Split Flow NTrial=30
Split Flow Tol=0.02
Split Flow Ratio=0.02
Log Output Level=0
Friction Slope Method=1
Unsteady Friction Slope Method=2
Unsteady Bridges Friction Slope Method=1
Global Log Level=0
CheckData=False
Run HTab=0
Run UNet=0
Run PostProcess=0
UNET Theta=0
UNET Theta Warmup=0
UNET ZTol=0
UNET ZSATol=0
UNET MxIter=0
UNET MaxInSteps=0
UNET DtIC=0
UNET DtMin=0
UNET MaxCRTS=0
UNET WFStab=0
UNET SFStab=0
UNET WFX=0
UNET SFX=0
UNET DSS MLevel=0
UNET DZMax Abort=0
UNET Convert EG Bridges=0
UNET Use Existing IB Tables=0
UNET Froude Limit=0
UNET Froude Power=0
Write IC File=0
Echo Input=False
Echo Output=False
Write Detailed=0

--- ManilaCr.f01 (steady flow) ---

Flow Title=USGS Regress. Eqn. (2010) - Western-Plateaus
Program Version=4.10
Number of Profiles= 1
Profile Names=P100yr
River Rch & RM=ManilaCr,Main            ,27159.6
    1146
River Rch & RM=ManilaCr,Main            ,19954.1
    1494
River Rch & RM=ManilaCr,Main            ,17048.1
    1571
River Rch & RM=ManilaCr,Main            ,16610.2
    1763
River Rch & RM=ManilaCr,Main            ,15272.7
    1804
River Rch & RM=ManilaCr,Main            ,14919.4
    2325
River Rch & RM=ManilaCr,Main            ,10653.4
    2449
River Rch & RM=ManilaCr,Main            ,6501.1
    2645
River Rch & RM=ManilaCr,Main            ,5039.3
    2711
River Rch & RM=ManilaCr,Main            ,28
    2905
Boundary for River Rch & Prof#=ManilaCr,Main            , 1
Up Type= 0
Dn Type= 1
Dn Known WS=584.9
DSS Import GetInterval= 0
DSS Import GetPeak= 0
DSS Import FillOption= 0

--- ManilaCr.g01 (geometry) ---

Geom Title=USGS 3m DEM
Program Version=4.10

River Reach=ManilaCr        ,Main
Reach XY= 30
      1742972.51      570942.382     1743259.874      570339.687
     1743375.072      569034.476     1743113.169      568414.797
     1741851.016      567164.797     1741331.919      565991.186
     1739999.084      564745.295     1740079.949      563803.632
     1739014.777      562728.569     1738140.946      561381.811
     1738400.565      560422.753     1737543.023      560098.513
     1737746.722      559499.416     1738367.765      558992.544
     1737997.654      558470.369     1738439.615      558119.689
     1737893.003      557774.353     1738122.049      557391.853
     1738027.379      556971.539     1737349.418      556349.598
     1737515.621      555801.045     1737486.409      555545.066
     1737143.416      555364.617     1737122.732      553486.823
     1737973.294      553095.265     1738970.846      553338.407
     1739216.192      552995.538     1738909.251      552470.149
     1738964.537       551778.89     1739499.618      551370.199

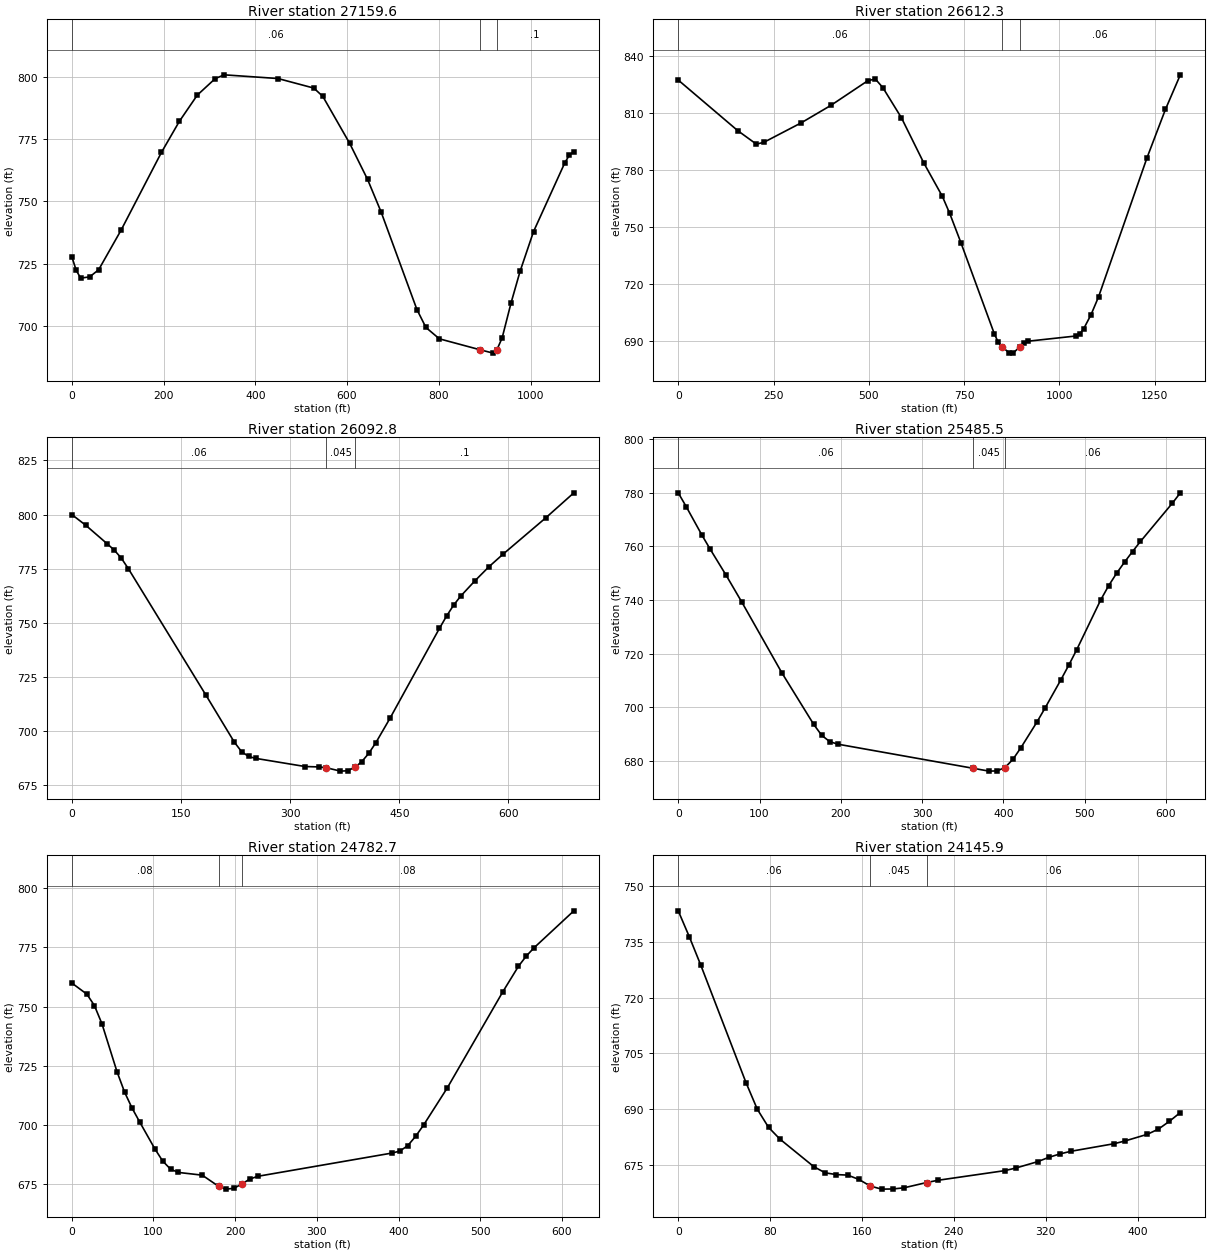
Type RM Length L Ch R = 1 ,27159.6 ,558.7,547.3,535.1
XS GIS Cut Line= 2
     1743835.756      571288.399     1742855.795      570801.419
#Sta/Elev= 30
       0  727.79     9.8   722.2    19.5  719.12    39.1  719.64    58.6   722.5
   107.5  738.45   195.4  769.74   234.5  782.26   273.6  792.82   312.6  799.47
   332.2  800.99   449.4   799.5   527.6  795.65   547.2  792.29   605.8  773.36
   644.8  758.84   674.2  745.77   752.3  706.46   771.9  699.25   801.2  694.68
   889.1  690.31   918.4  688.92   925.9  689.98     938  695.04   957.5  709.18
     977  721.81  1006.4  737.85  1074.8  765.64  1084.5  768.64  1094.3  770.08
#Mann= 3 , 0 , 0
       0     .06       0   889.1    .045       0   925.9      .1       0
Bank Sta=889.1,925.9
XS Rating Curve= 0 ,0
Exp/Cntr=0.3,0.1

Type RM Length L Ch R = 1 ,26612.3 ,517.7,519.5,521.4
XS GIS Cut Line= 3
     1744135.387       570383.21     1743062.175      570396.195
      1742860.87        570258.4
#Sta/Elev= 30
       0  827.26   156.1  800.68   204.9   793.6   224.4  794.53     322  804.71
     400  813.89   497.6  826.94   517.1  827.79   536.6  823.34   585.4   807.5
     644   783.8   692.8  766.22   712.3  757.17   741.6  741.84   829.4  693.89
   839.1  689.74   848.9  687.15   868.4  684.02   878.2  683.82   896.8  687.19
   907.4  689.38   917.2  690.07    1044  692.83  1053.8  693.96  1063.5  696.55
    1083  704.03  1102.6  713.32  1229.4   786.2  1278.2  811.84  1317.2     830
#Mann= 3 , 0 , 0
       0     .06       0   848.9    .045       0   896.8     .06       0
Bank Sta=848.9,896.8
XS Rating Curve= 0 ,0
Exp/Cntr=0.3,0.1

Type RM Length L Ch R = 1 ,26092.8 ,606.4,607.3,607.7
XS GIS Cut Line= 2
     1743620.928      569904.971     1742932.854      569856.721
#Sta/Elev= 30
       0     800    19.4  794.98    48.6  786.51    58.3  783.62      68   779.9
    77.7  775.03   184.6  716.52   223.4  694.96   233.2  690.65   242.9  688.38
   252.6  687.51   320.6  683.74     340  683.56   349.7  683.18   369.2  681.62
   378.9  681.78   389.5  683.49   398.3  685.95     408  689.79   417.7  694.69
   437.2  705.99   505.2  747.51   514.9  753.13   524.6  758.18   534.3  762.34
   553.8  769.38   573.2  775.92   592.6  781.72   650.9  798.37   689.8     810
#Mann= 3 , 0 , 0
       0     .06       0   349.7    .045       0   389.5      .1       0
Bank Sta=349.7,389.5
XS Rating Curve= 0 ,0
Exp/Cntr=0.3,0.1

Type RM Length L Ch R = 1 ,25485.5 ,717.4,702.8,688.2
XS GIS Cut Line= 2
     1743693.725      569316.518     1743079.115      569254.465
#Sta/Elev= 30
       0  780.02     9.8  774.87    29.4  764.09    39.2  759.02    58.8  749.29
    78.4  739.11   127.5  712.78   166.7  693.51   176.5  689.45   186.3  687.11
   196.1  686.15   362.8  677.13   382.4  676.07   392.2  676.15     402  677.41
   411.8  680.48   421.6  684.83   441.2  694.35     451  699.48   470.7  710.14
   480.5  715.66   490.3  721.46   519.7  739.98   529.5  745.31   539.3  749.97
   549.1  754.15   558.9  758.09   568.7  761.86   607.9  776.15   617.7     780
#Mann= 3 , 0 , 0
       0     .06       0   362.8    .045       0     402     .06       0
Bank Sta=362.8,402
XS Rating Curve= 0 ,0
Exp/Cntr=0.3,0.1

Type RM Length L Ch R = 1 ,24782.7 ,651.9,636.8,621.7
XS GIS Cut Line= 3
      1743359.88      568512.478     1743280.051      568575.332
     1742841.666      568841.679
#Sta/Elev= 30
       0     760    18.5  755.27    27.7  750.49      37  742.72    55.4   722.5
    64.7  713.86    73.9  707.09    83.1  701.32   101.6     690   111.3  684.79
     121  681.34   130.6  679.98   159.7  678.83   179.7  674.12   188.7  672.93
   198.4  673.27   208.1  675.09   217.7  677.13   227.4  678.33     392  688.17
   401.6  688.99   411.3  691.31     421  695.26   430.7  700.01   459.7   715.7
   527.4  756.14   546.8  767.06   556.5  771.43   566.2  774.97   614.6  790.48
#Mann= 3 , 0 , 0
       0     .08       0   179.7    .045       0   208.1     .08       0
Bank Sta=179.7,208.1
XS Rating Curve= 0 ,0
Exp/Cntr=0.3,0.1

Type RM Length L Ch R = 1 ,24145.9 ,37.3,37.4,37.3
XS GIS Cut Line= 3
     1742849.318      568007.612     1742758.129       568246.39
     1742623.532      568367.944
#Sta/Elev= 30
       0  743.31     9.8  736.22    19.7  728.65      59  697.11    68.8  689.98
    78.6   685.1    88.5  681.94     118  674.53   127.8  672.88   137.6   672.4
   147.5  672.26   157.3  671.09   167.1  669.32     177  668.49   186.8  668.53
   196.6  668.85   216.3  670.27   226.1  670.87   284.2  673.46   293.8  674.16
   312.9  675.88   322.4  677.02     332  677.93   341.5  678.65   379.7  680.72
   389.2  681.47   408.3  683.23   417.9  684.62   427.4   686.7     437  689.08
#Mann= 3 , 0 , 0
       0     .06       0   167.1    .045       0   216.3     .06       0
Bank Sta=167.1,216.3
XS Rating Curve= 0 ,0
Exp/Cntr=0.3,0.1

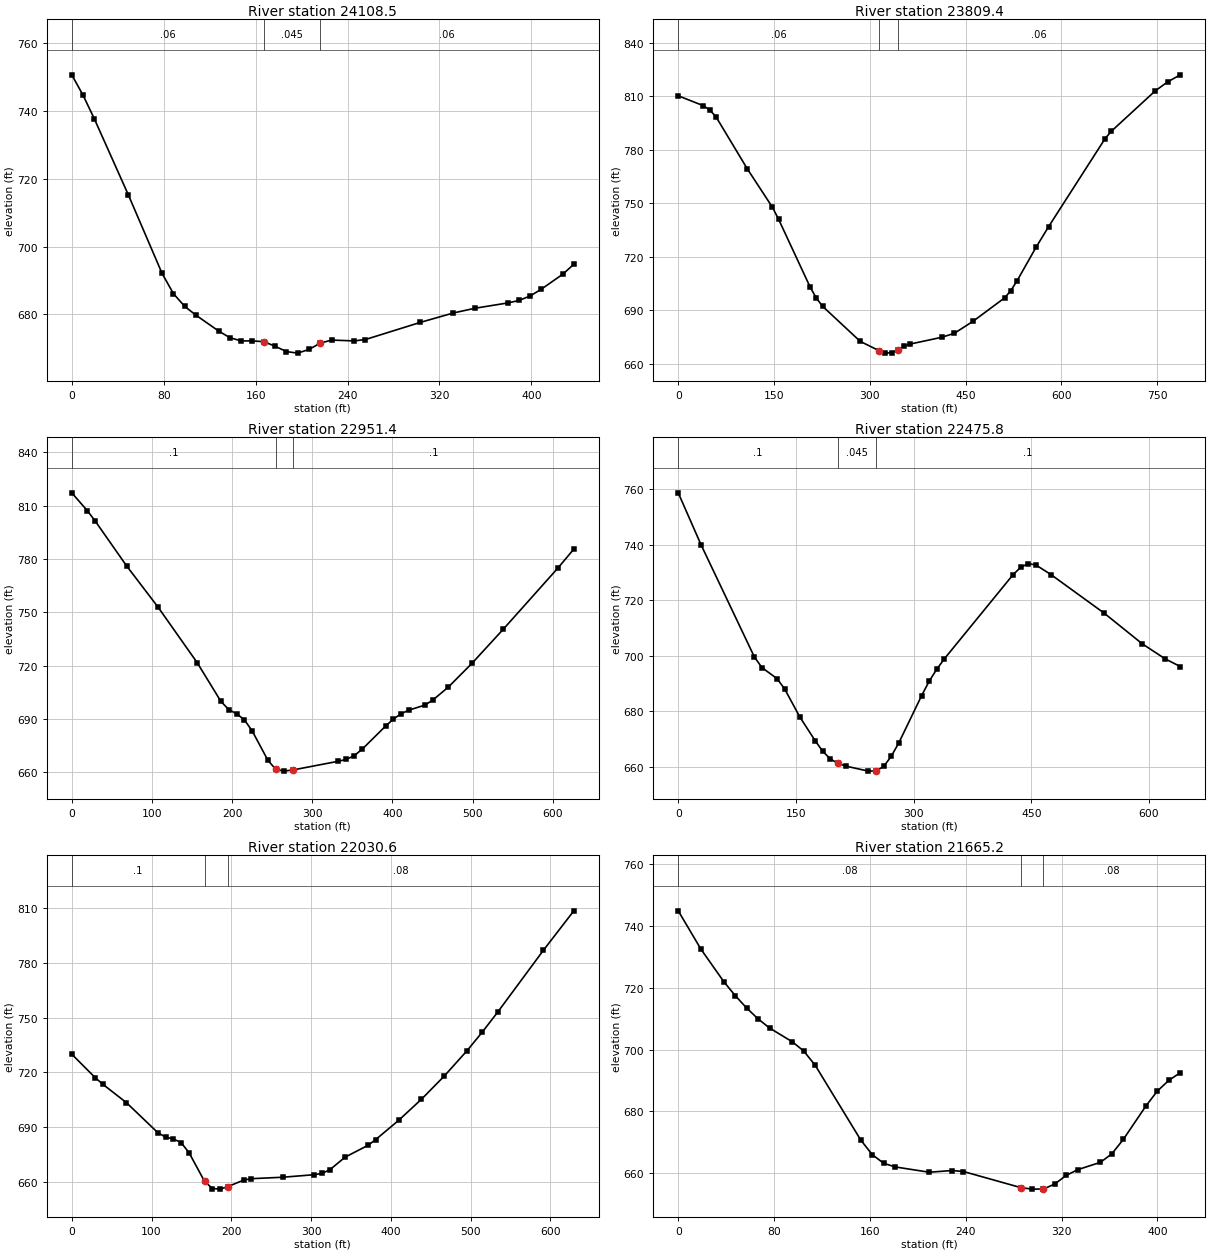
Type RM Length L Ch R = 1 ,24108.5 ,288.9,299.1,309.2
XS GIS Cut Line= 3
     1742823.271      567972.878     1742732.082      568211.656
     1742597.486      568333.209
#Sta/Elev= 30
       0  750.62     9.8  744.63    19.7  737.61    49.2  715.28    78.6   692.1
    88.5  686.13    98.3  682.38   108.1  679.79   127.8  675.13   137.6  673.16
   147.5  672.21   157.3  672.21   167.1  671.99     177  670.64   186.8  669.07
   196.6  668.61   206.4  669.69   216.3  671.55   226.1  672.46   245.8  672.21
   255.6  672.62   303.3  677.66     332  680.43     351  681.84   379.7  683.41
   389.2  684.12   398.8  685.43   408.3  687.36   427.4  691.87     437   694.8
#Mann= 3 , 0 , 0
       0     .06       0   167.1    .045       0   216.3     .06       0
Bank Sta=167.1,216.3
XS Rating Curve= 0 ,0
Exp/Cntr=0.3,0.1

Type RM Length L Ch R = 1 ,23809.4 ,853.3,858,862.3
XS GIS Cut Line= 2
     1742778.793      567721.559     1742207.844      568262.039
#Sta/Elev= 30
       0  810.22    39.3  804.66    49.1  802.32      59   798.5   108.1  769.26
   147.4  747.73   157.2   740.9   206.4  703.01   216.2  696.75     226  692.13
     285  672.43   314.5  667.21   324.3  665.84   334.1  666.09     344  667.78
   353.8   669.8   363.6  670.96   412.8  674.74   432.4  676.97   461.9  683.77
     511  696.82   520.8  700.89   530.7  706.51   560.2  725.16   579.8   736.7
   668.3  786.14   678.1  790.29   746.9  812.96   766.5  818.05   786.2  821.98
#Mann= 3 , 0 , 0
       0     .06       0   314.5    .045       0     344     .06       0
Bank Sta=314.5,344
XS Rating Curve= 0 ,0
Exp/Cntr=0.3,0.1

Type RM Length L Ch R = 1 ,22951.4 ,473.9,475.6,477.1
XS GIS Cut Line= 2
     1742214.434      567161.462     1741684.744      567495.722
#Sta/Elev= 30
       0  817.29    19.6  807.14    29.4  801.29    68.5   776.1   107.6  752.96
   156.6  721.58   185.9  699.98   195.7  695.31   205.5  692.97   215.3  689.53
   225.1  683.23   244.7  666.68   254.4  661.68   264.2  660.63   275.9  661.29
   332.7   666.2   342.5  667.24   352.3  669.36   362.1  672.89   391.5     686
   401.2  689.94     411  692.98   420.8  695.01   440.4  697.79   450.2  700.56
   469.8  707.96   499.1  721.25   538.3  740.52   606.8  775.14   626.3  785.64
#Mann= 3 , 0 , 0
       0      .1       0   254.4    .045       0   275.9      .1       0
Bank Sta=254.4,275.9
XS Rating Curve= 0 ,0
Exp/Cntr=0.3,0.1

Type RM Length L Ch R = 1 ,22475.8 ,442.1,445.2,448.3
XS GIS Cut Line= 2
     1741947.455      566801.097     1741380.865      567098.451
#Sta/Elev= 30
       0  758.69    29.1  739.94      97  699.55   106.6   695.7     126  691.69
   135.7  687.94   155.1  677.82   174.5  669.34   184.2  665.49   193.9  662.74
   203.6  661.15   213.3  660.19   242.4  658.36   252.1  658.45   261.8  660.03
   271.5  663.72   281.2  668.59   310.2  685.58   319.9  690.82   329.6  695.14
   339.3  698.89   426.6  729.14   436.3   731.8     446  733.17   455.7   732.7
   475.1  729.21   542.9   715.3   591.4  704.26   620.5  698.85   639.9  696.06
#Mann= 3 , 0 , 0
       0      .1       0   203.6    .045       0   252.1      .1       0
Bank Sta=203.6,252.1
XS Rating Curve= 0 ,0
Exp/Cntr=0.3,0.1

Type RM Length L Ch R = 1 ,22030.6 ,367.4,365.5,362.8
XS GIS Cut Line= 3
     1741752.165       566436.59     1741430.831      566555.764
      1741144.29      566562.256
#Sta/Elev= 30
       0  729.98    29.4  717.11    39.2   713.4    68.5  703.41   107.7  687.02
   117.5  684.52   127.3  683.53   137.1  681.48   146.9  676.01   166.5  660.21
   176.3  656.32     186  655.99   195.8  657.38   215.4  660.96   225.2  661.72
   264.4  662.51   303.6  663.89   313.4   664.6   323.1   666.5   342.7  673.54
   371.4  680.04   380.9  683.14   409.6  693.67   438.3  705.28   466.9     718
   495.6  731.99   514.7  742.19   533.8  753.03   591.1  786.94   629.3   808.6
#Mann= 3 , 0 , 0
       0      .1       0   166.5    .045       0   195.8     .08       0
Bank Sta=166.5,195.8
XS Rating Curve= 0 ,0
Exp/Cntr=0.3,0.1

Type RM Length L Ch R = 1 ,21665.2 ,613.1,609.9,606.4
XS GIS Cut Line= 3
     1741634.921      566008.746     1741535.058       566123.79
     1741295.327      566240.814
#Sta/Elev= 30
       0  744.84      19  732.42    38.1  721.92    47.6  717.42    57.1  713.44
    66.6  709.94    76.2  706.98    95.2  702.52   104.7  699.56   114.3  694.95
   152.3  670.81   161.9  666.08   171.4  663.28   180.9   662.1   209.5  660.37
   228.6  660.92   238.1   660.6   285.7  655.43   295.2  654.91   304.8  654.94
   314.3  656.56   323.8  659.33   333.4  661.19   352.4  663.57   361.9  666.29
   371.5  670.96   390.5  681.84     400  686.63   409.6  690.08   419.1  692.54
#Mann= 3 , 0 , 0
       0     .08       0   285.7    .045       0   304.8     .08       0
Bank Sta=285.7,304.8
XS Rating Curve= 0 ,0
Exp/Cntr=0.3,0.1

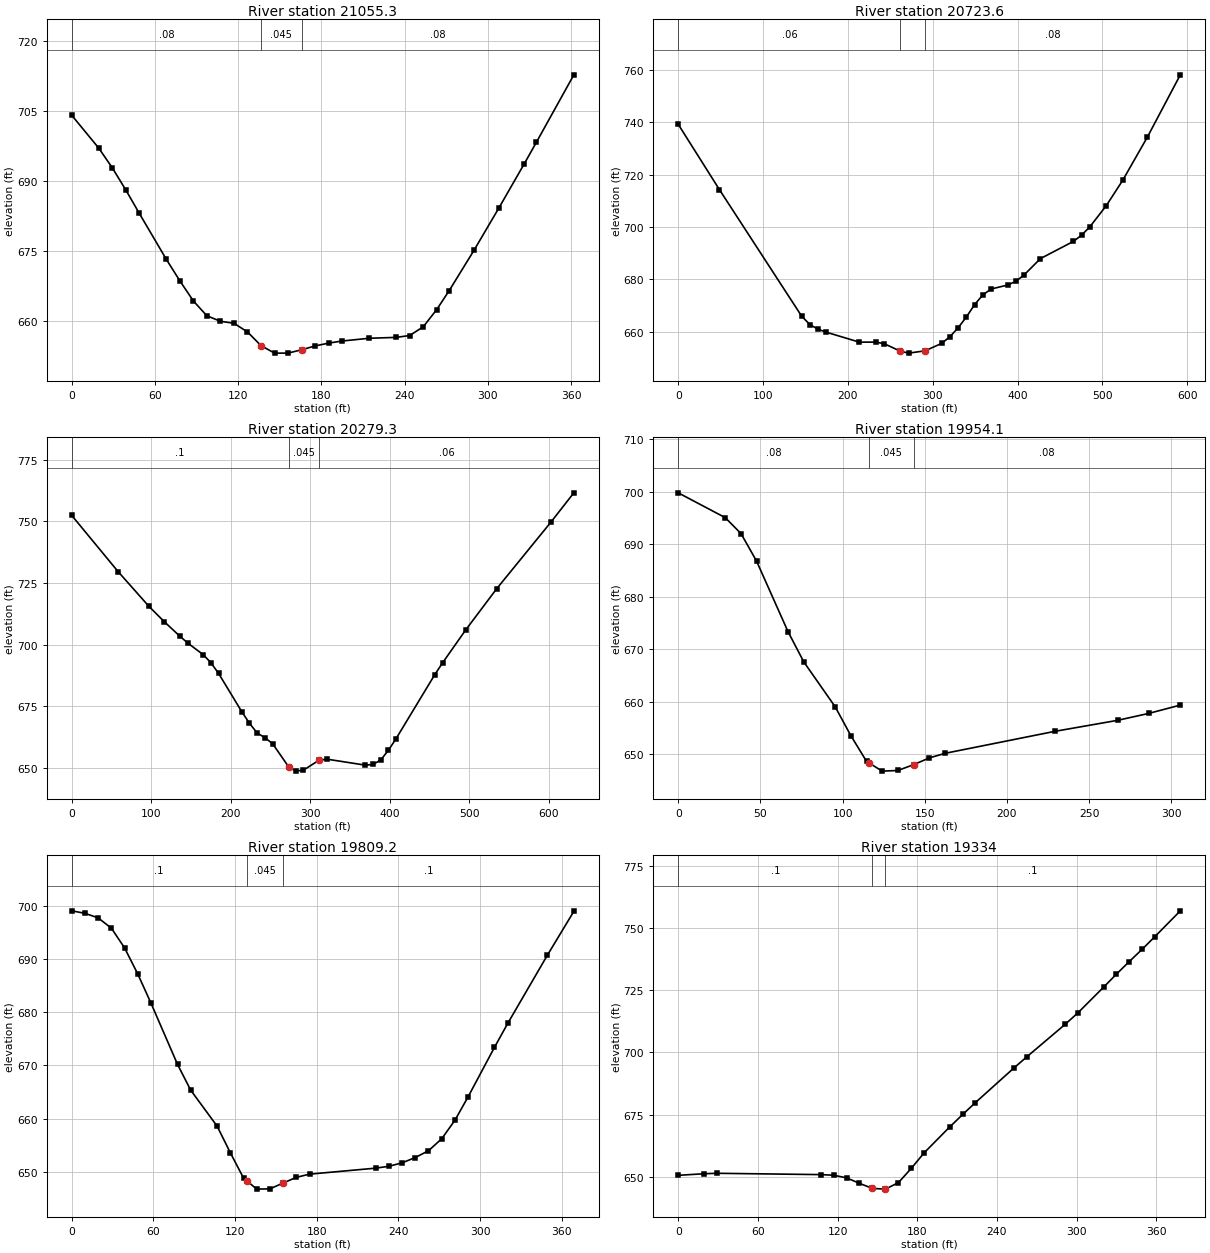
Type RM Length L Ch R = 1 ,21055.3 ,333.6,331.7,329.6
XS GIS Cut Line= 3
     1741128.063      565717.336     1740908.806      565862.762
     1740815.461      565895.317
#Sta/Elev= 30
       0  704.14    19.5  697.08    29.2  692.87      39  688.09    48.7  683.08
    68.2   673.2      78  668.57    87.7  664.27    97.4   661.1   107.2  659.92
   116.9  659.49   126.7  657.63   136.4   654.7   146.2  653.08   155.9  653.08
   165.7   653.8   175.4  654.62   185.2  655.23   194.9  655.68   214.4  656.27
   233.9  656.46   243.6  656.86   253.4  658.73   263.1  662.42   272.1  666.49
   290.1   675.2     308  684.27     326   693.6     335  698.35     362  712.83
#Mann= 3 , 0 , 0
       0     .08       0   136.4    .045       0   165.7     .08       0
Bank Sta=136.4,165.7
XS Rating Curve= 0 ,0
Exp/Cntr=0.3,0.1

Type RM Length L Ch R = 1 ,20723.6 ,446.8,444.4,442.1
XS GIS Cut Line= 2
     1741003.273      565383.523     1740538.704      565750.349
#Sta/Elev= 30
       0  739.29    48.5  714.33   145.6  665.85   155.3  662.66     165  660.87
   174.7  659.75   213.5  655.96   232.9  655.97   242.6  655.39     262  652.48
   271.7  651.76   291.1  652.65   310.5  655.48   320.2  658.02   329.9  661.43
   339.6  665.54   349.3  670.28     359     674   368.8  676.28   388.2   677.8
   397.9   679.2   407.6  681.62     427  687.92   465.8  694.49   475.5  696.88
   485.2  700.06   504.6  708.16     524  717.87   553.1  734.42   591.9  758.22
#Mann= 3 , 0 , 0
       0     .06       0     262    .045       0   291.1     .08       0
Bank Sta=262,291.1
XS Rating Curve= 0 ,0
Exp/Cntr=0.3,0.1

Type RM Length L Ch R = 1 ,20279.3 ,325,325.2,325.3
XS GIS Cut Line= 2
     1740726.742       565026.63      1740276.93      565469.434
#Sta/Elev= 30
       0  752.42    58.3  729.63    97.1  715.53   116.5  709.29     136  703.43
   145.7  700.73   165.1  696.02   174.8  692.76   184.5  688.42   213.6  672.93
   223.4  668.17   233.1  664.23   242.8  662.33   252.5  659.88   272.5  650.58
   281.6  648.77   291.3  649.17   310.7  653.17   320.4  653.64     369   651.2
   378.7  651.48   388.4  653.28   398.1  657.23   407.8  661.98   456.4   687.9
   466.1  692.64   495.2  705.99   534.1  722.68   602.1   749.6   631.2  761.59
#Mann= 3 , 0 , 0
       0      .1       0   272.5    .045       0   310.7     .06       0
Bank Sta=272.5,310.7
XS Rating Curve= 0 ,0
Exp/Cntr=0.3,0.1

Type RM Length L Ch R = 1 ,19954.1 ,143.9,144.9,146.1
XS GIS Cut Line= 2
     1740379.206      564914.102     1740159.945      565126.821
#Sta/Elev= 19
       0  699.79    28.6  695.06    38.2  692.02    47.7  686.75    66.8  673.33
    76.4  667.56    95.5     659     105  653.52   114.6  648.59   116.2  648.28
   124.1  646.74   133.6  646.86   143.2  647.97   152.8  649.26   162.3  650.13
   229.1  654.32   267.3  656.42   286.4  657.75   305.5  659.33
#Mann= 3 , 0 , 0
       0     .08       0   116.2    .045       0   143.2     .08       0
Bank Sta=116.2,143.2
XS Rating Curve= 0 ,0
Exp/Cntr=0.3,0.1

Type RM Length L Ch R = 1 ,19809.2 ,461,475.1,488.5
XS GIS Cut Line= 2
     1740288.042      564809.899     1740011.203       565053.66
#Sta/Elev= 30
       0  699.11     9.7  698.64    19.4  697.78    29.1  695.84    38.8  692.13
    48.5  687.21    58.2  681.72    77.7  670.19    87.4  665.33   106.8  658.56
   116.5  653.55   126.2  648.78   128.5  648.29   135.9   646.7   145.6  646.75
   155.3  647.85     165  648.92   174.7  649.52   223.3  650.65     233     651
   242.7  651.65   252.4  652.65   262.1  653.93   271.8  656.18   281.5  659.66
   291.2  664.08   310.6  673.41   320.3   677.9   349.4  690.73   368.9  699.01
#Mann= 3 , 0 , 0
       0      .1       0   128.5    .045       0   155.3      .1       0
Bank Sta=128.5,155.3
XS Rating Curve= 0 ,0
Exp/Cntr=0.3,0.1

Type RM Length L Ch R = 1 ,19334   ,210,247.7,285.2
XS GIS Cut Line= 3
     1740075.328       564512.49     1739891.468      564535.112
     1739710.856      564602.827
#Sta/Elev= 25
       0  650.58    19.5  651.22    29.2   651.4   107.2  650.87     117  650.62
   126.8  649.56   136.5  647.35   146.2  645.32     156  645.03   165.8  647.64
   175.5  653.38   185.2  659.64   204.5  670.06   214.2  675.04   223.8  679.83
   252.8  693.75   262.4  698.18   291.3  711.26     301  715.92   320.3  726.22
   329.9  731.43   339.6  736.51   349.2   741.4   358.8  746.48   378.1  756.94
#Mann= 3 , 0 , 0
       0      .1       0   146.2    .045       0     156      .1       0
Bank Sta=146.2,156
XS Rating Curve= 0 ,0
Exp/Cntr=0.3,0.1

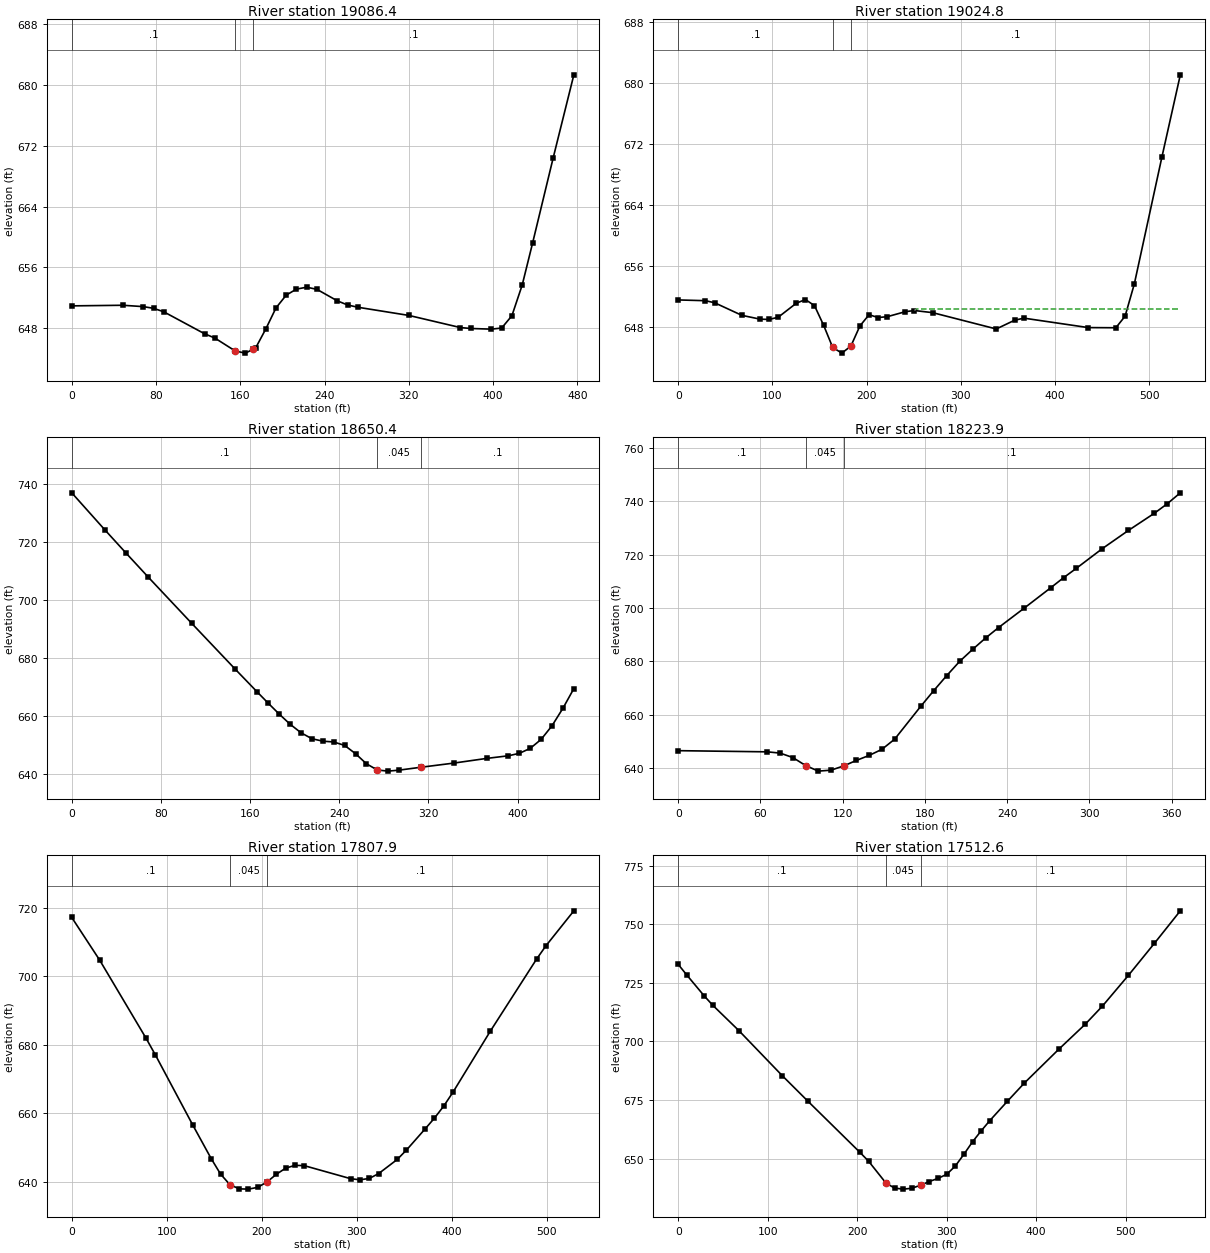
Type RM Length L Ch R = 1 ,19086.4 ,61.7,61.5,61
XS GIS Cut Line= 3
     1740003.695      564479.924     1739979.839       564160.82
      1739830.06      564115.224
#Sta/Elev= 30
       0   650.9    48.5  650.98    67.9   650.8    77.6  650.58    87.3  650.12
   126.1  647.22   135.8  646.66   155.2  644.95   164.8  644.67   172.2  645.18
   174.5  645.34   184.2  647.86   193.9  650.64   203.6  652.32   213.3  653.11
     223  653.36   232.7  653.08   252.1  651.56   261.8  651.02   271.5  650.72
     320  649.64   368.9  648.04   378.7  647.92   398.3  647.83   408.1  647.98
   417.8   649.6   427.6  653.66   437.4  659.16     457  670.42   476.6  681.36
#Mann= 3 , 0 , 0
       0      .1       0   155.2    .045       0   172.2      .1       0
Bank Sta=155.2,172.2
XS Rating Curve= 0 ,0
Exp/Cntr=0.3,0.1

Type RM Length L Ch R = 1 ,19024.8 ,412.2,374.5,337.1
XS GIS Cut Line= 3
     1740060.136      564466.903      1740034.11      564130.434
     1739845.257      564080.493
#Sta/Elev= 30
       0  651.56    28.9  651.46    38.6  651.19    67.5  649.54    86.8  649.04
    96.4     649   106.1  649.29   125.4  651.14     135  651.61   144.6  650.81
   154.3  648.23   163.9  645.33   173.6  644.58   183.2   645.5   192.8  648.15
   202.5  649.62   212.1  649.25   221.8  649.36     241  650.02   250.7  650.17
     270  649.89   337.5  647.75     357   648.9   366.8  649.17   435.2  647.93
   464.4  647.91   474.2  649.43     484  653.66   513.3  670.33   532.8   681.1
#Mann= 3 , 0 , 0
       0      .1       0   163.9    .045       0   183.2      .1       0
#XS Ineff= 2 , 0
                          251.37          650.33
Permanent Ineff=
       F       F
Bank Sta=163.9,183.2
XS Rating Curve= 0 ,0
Exp/Cntr=0.3,0.1

Type RM Length L Ch R = 1 ,18650.4 ,432.8,426.5,419.5
XS GIS Cut Line= 2
     1740355.393       563971.99     1739905.898      564002.352
#Sta/Elev= 30
       0  736.82    29.4  724.18      49  715.93    68.6  707.78   107.7  691.81
   146.9  675.95   166.5  668.15   176.3  664.31   186.1  660.58   195.9  657.08
   205.7  654.13   215.5  652.07   225.3  651.23     235  650.96   244.8  649.78
   254.6  646.92   264.4  643.44   274.2  641.29     284  640.91   293.8  641.26
   313.4  642.25   342.8  643.68   372.2  645.29   391.8   646.2   401.6  647.05
   411.3  648.74   421.1  651.83   430.9  656.54   440.7  662.57   450.5  669.35
#Mann= 3 , 0 , 0
       0      .1       0   274.2    .045       0   313.4      .1       0
Bank Sta=274.2,313.4
XS Rating Curve= 0 ,0
Exp/Cntr=0.3,0.1

Type RM Length L Ch R = 1 ,18223.9 ,424.7,416,407.2
XS GIS Cut Line= 3
      1740016.78      563607.279     1739868.865        563662.6
      1739710.69      563798.285
#Sta/Elev= 28
       0  646.43      65  645.99    74.3  645.52    83.6  643.85    92.9  640.86
   102.2  638.75   111.5  639.12   120.8  640.72     130  642.78   139.3  644.65
   148.6  646.93   157.9  650.75   176.9  663.06   186.3   668.9   195.8  674.56
   205.3  679.94   214.8  684.46   224.2   688.7   233.7  692.64   252.6  700.01
   271.6  707.52   281.1  711.35   290.5   714.9   309.5  722.31   328.4  729.09
   347.4  735.56   356.8  739.13   366.3  743.22
#Mann= 3 , 0 , 0
       0      .1       0    92.9    .045       0   120.8      .1       0
Bank Sta=92.9,120.8
XS Rating Curve= 0 ,0
Exp/Cntr=0.3,0.1

Type RM Length L Ch R = 1 ,17807.9 ,296.5,295.3,293.8
XS GIS Cut Line= 2
     1739863.786      563156.036     1739473.025      563512.014
#Sta/Elev= 30
       0  717.15    29.4  704.71    78.3   681.9    88.1  677.04   127.2  656.74
   146.8  646.84   156.6  642.36   166.4  639.27   176.2  638.03     186  637.95
   195.8  638.47   205.6  640.05   215.4  642.28   225.1  644.05   234.9  644.88
   244.7   644.8   293.7  640.99   303.4  640.67   313.2  641.06     323  642.46
   342.6  646.59   352.4  649.35     372   655.5   381.8  658.64   391.6  662.16
   401.3  666.19   440.5  683.93   489.4  705.03   499.2  708.89   528.6  719.09
#Mann= 3 , 0 , 0
       0      .1       0   166.4    .045       0   205.6      .1       0
Bank Sta=166.4,205.6
XS Rating Curve= 0 ,0
Exp/Cntr=0.3,0.1

Type RM Length L Ch R = 1 ,17512.6 ,468.4,464.5,459.1
XS GIS Cut Line= 2
     1739660.609      562953.047     1739268.108      563354.176
#Sta/Elev= 30
       0  732.89     9.7   728.3      29  719.46    38.7  715.41    67.7  704.66
   116.1  685.46   145.1  674.43   203.2  652.61   212.9  648.81   232.2  639.53
   241.9  637.38   251.6  636.95   261.2  637.32   270.9  638.64   280.6   640.2
   290.3  641.52     300  643.26   309.6  646.76   319.3  651.82     329  657.18
   338.7  661.87   348.3  666.22   367.7  674.37     387  682.29   425.8  696.83
   454.8   707.3   474.1  715.08   503.2  728.23   532.2  741.87   561.2  755.77
#Mann= 3 , 0 , 0
       0      .1       0   232.2    .045       0   270.9      .1       0
Bank Sta=232.2,270.9
XS Rating Curve= 0 ,0
Exp/Cntr=0.3,0.1

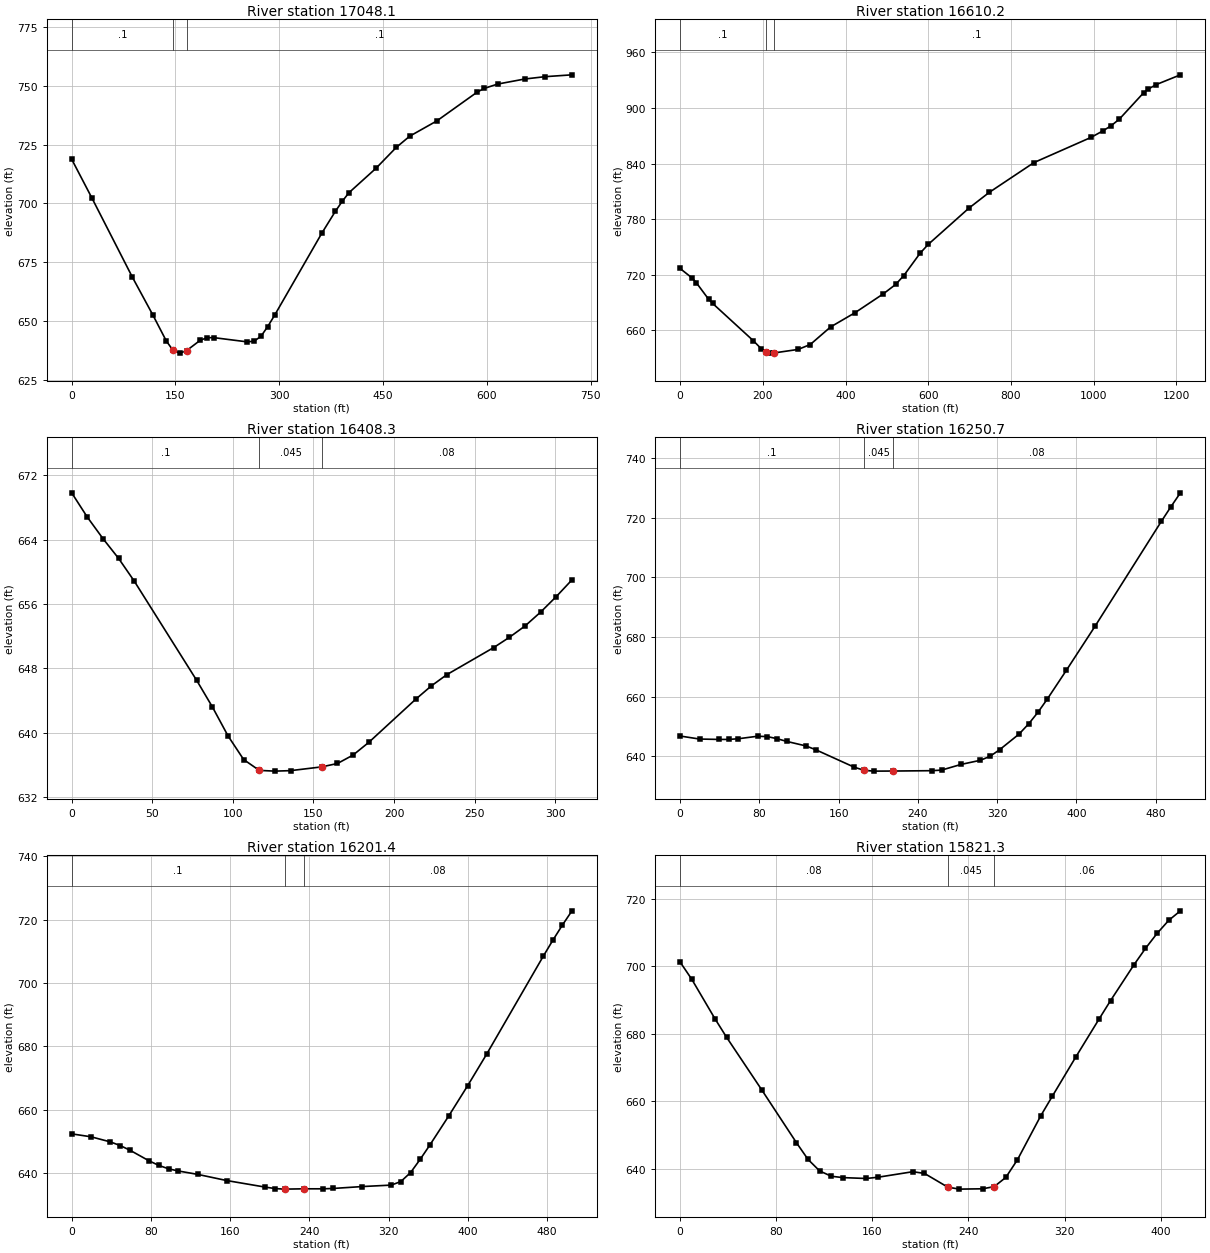
Type RM Length L Ch R = 1 ,17048.1 ,424.3,437.9,450.9
XS GIS Cut Line= 2
     1739242.106      562678.634     1738850.033      563286.212
#Sta/Elev= 30
       0  718.76    29.3  702.25    87.9  668.56   117.3  652.61   136.8  641.54
   146.6  637.53   156.4  636.39   166.1  637.46   185.7  641.83   195.4  642.92
   205.2  642.98   254.1  641.16   263.8   641.5   273.6  643.53   283.4   647.7
   293.2  652.43   361.6  687.37   381.1  696.62   390.9  700.81   400.6  704.49
   439.7  714.87     469  723.74   488.6  728.55   527.7  735.02   586.3  747.31
   596.1  748.83   615.6  750.68   654.7  752.83     684  753.82   723.1  754.61
#Mann= 3 , 0 , 0
       0      .1       0   146.6    .045       0   166.1      .1       0
Bank Sta=146.6,166.1
XS Rating Curve= 0 ,0
Exp/Cntr=0.3,0.1

Type RM Length L Ch R = 1 ,16610.2 ,202.4,201.9,201.5
XS GIS Cut Line= 2
     1739079.752      562404.239     1737973.074      562893.244
#Sta/Elev= 30
       0  726.76    29.5   716.3    39.4   711.3    68.9  693.58    78.7  689.04
   177.1  648.78   196.7  639.91   206.6  636.57   216.4   635.4   226.2  635.54
   285.3  639.38   314.8   644.7     364  663.68     423  679.03   491.8  699.51
   521.3  709.54     541  719.14   580.4  743.26     600  752.74   698.4   791.9
   747.6  808.91   855.8   841.1   993.5  868.22    1023  875.43  1042.7  880.96
  1062.4  888.06  1121.4  916.65  1131.2  920.17  1150.9  925.17  1209.9  935.81
#Mann= 3 , 0 , 0
       0      .1       0   206.6    .045       0   226.2      .1       0
Bank Sta=206.6,226.2
XS Rating Curve= 0 ,0
Exp/Cntr=0.3,0.1

Type RM Length L Ch R = 1 ,16408.3 ,152.1,157.6,163.1
XS GIS Cut Line= 2
     1738891.986      562265.239     1738610.647      562396.334
#Sta/Elev= 25
       0  669.81     9.7  666.79    19.4  664.12    29.1  661.66    38.8  658.84
    77.6  646.48    87.3  643.19      97  639.59   106.7  636.65   116.4   635.3
   126.1  635.21   135.8  635.27   155.2  635.74   164.9  636.16   174.6  637.21
   184.3  638.78   213.4  644.14   223.1   645.8   232.8  647.21   261.9  650.58
   271.6  651.85   281.3  653.26     291  654.99   300.7  656.92   310.4  658.99
#Mann= 3 , 0 , 0
       0      .1       0   116.4    .045       0   155.2     .08       0
Bank Sta=116.4,155.2
XS Rating Curve= 0 ,0
Exp/Cntr=0.3,0.1

Type RM Length L Ch R = 1 ,16250.7 ,47.2,49.3,58.1
XS GIS Cut Line= 3
     1738899.809      562144.546     1738564.639      562213.118
     1738413.551      562273.889
#Sta/Elev= 30
       0  646.77    19.6  645.76    39.1  645.63    48.9  645.63    58.6  645.85
    78.2   646.7      88  646.58    97.8  645.88   107.5  644.98   127.1  643.44
   136.8  642.19   175.9   636.3   185.7  635.28   195.5     635     215  635.03
   254.1  635.15   263.9  635.34   283.5  637.24     303  638.63   312.8  639.95
   322.6   642.2   342.1  647.41   351.7   650.8   361.3  654.77   370.8  659.24
     390  668.86   418.8  683.56   485.8  718.77   495.4  723.64     505  728.32
#Mann= 3 , 0 , 0
       0      .1       0   185.7    .045       0     215     .08       0
Bank Sta=185.7,215
XS Rating Curve= 0 ,0
Exp/Cntr=0.3,0.1

Type RM Length L Ch R = 1 ,16201.4 ,392,380,361.1
XS GIS Cut Line= 3
     1738889.392      562104.603     1738554.222      562173.176
     1738403.134      562233.947
#Sta/Elev= 30
       0  652.42    19.6  651.49    39.1  649.88    48.9  648.74    58.6   647.3
    78.2   643.9      88  642.47    97.8   641.4   107.5  640.72   127.1  639.65
   156.4   637.7   195.5  635.62   205.3  635.17     215  634.99   234.6  635.09
   254.1  635.09   263.9   635.2   293.2   635.8   322.6  636.26   332.3  637.39
   342.1  640.22   351.7  644.35   361.3  648.78   380.4  657.97   399.6  667.56
   418.8  677.52   476.2  708.54   485.8  713.54   495.4   718.3     505  722.76
#Mann= 3 , 0 , 0
       0      .1       0     215    .045       0   234.6     .08       0
Bank Sta=215,234.6
XS Rating Curve= 0 ,0
Exp/Cntr=0.3,0.1

Type RM Length L Ch R = 1 ,15821.3 ,230.1,222.9,214.4
XS GIS Cut Line= 2
     1738608.304      561740.041      1738271.82      561985.314
#Sta/Elev= 30
       0  701.21     9.7  696.11      29  684.42    38.7  678.92    67.8  663.43
    96.8  647.72   106.5  642.74   116.2  639.32   125.9  637.76   135.6  637.36
   154.9   637.1   164.6  637.47   193.7  639.11   203.4   638.6   222.7  634.55
   232.4  633.95   251.8  634.05   261.4  634.69   271.1  637.42   280.8  642.67
   300.2  655.69   309.9  661.53   329.2  673.01   348.6  684.27   358.3  689.81
   377.7  700.37   387.3  705.23     397   709.7   406.7  713.56   416.4  716.38
#Mann= 3 , 0 , 0
       0     .08       0   222.7    .045       0   261.4     .06       0
Bank Sta=222.7,261.4
XS Rating Curve= 0 ,0
Exp/Cntr=0.3,0.1

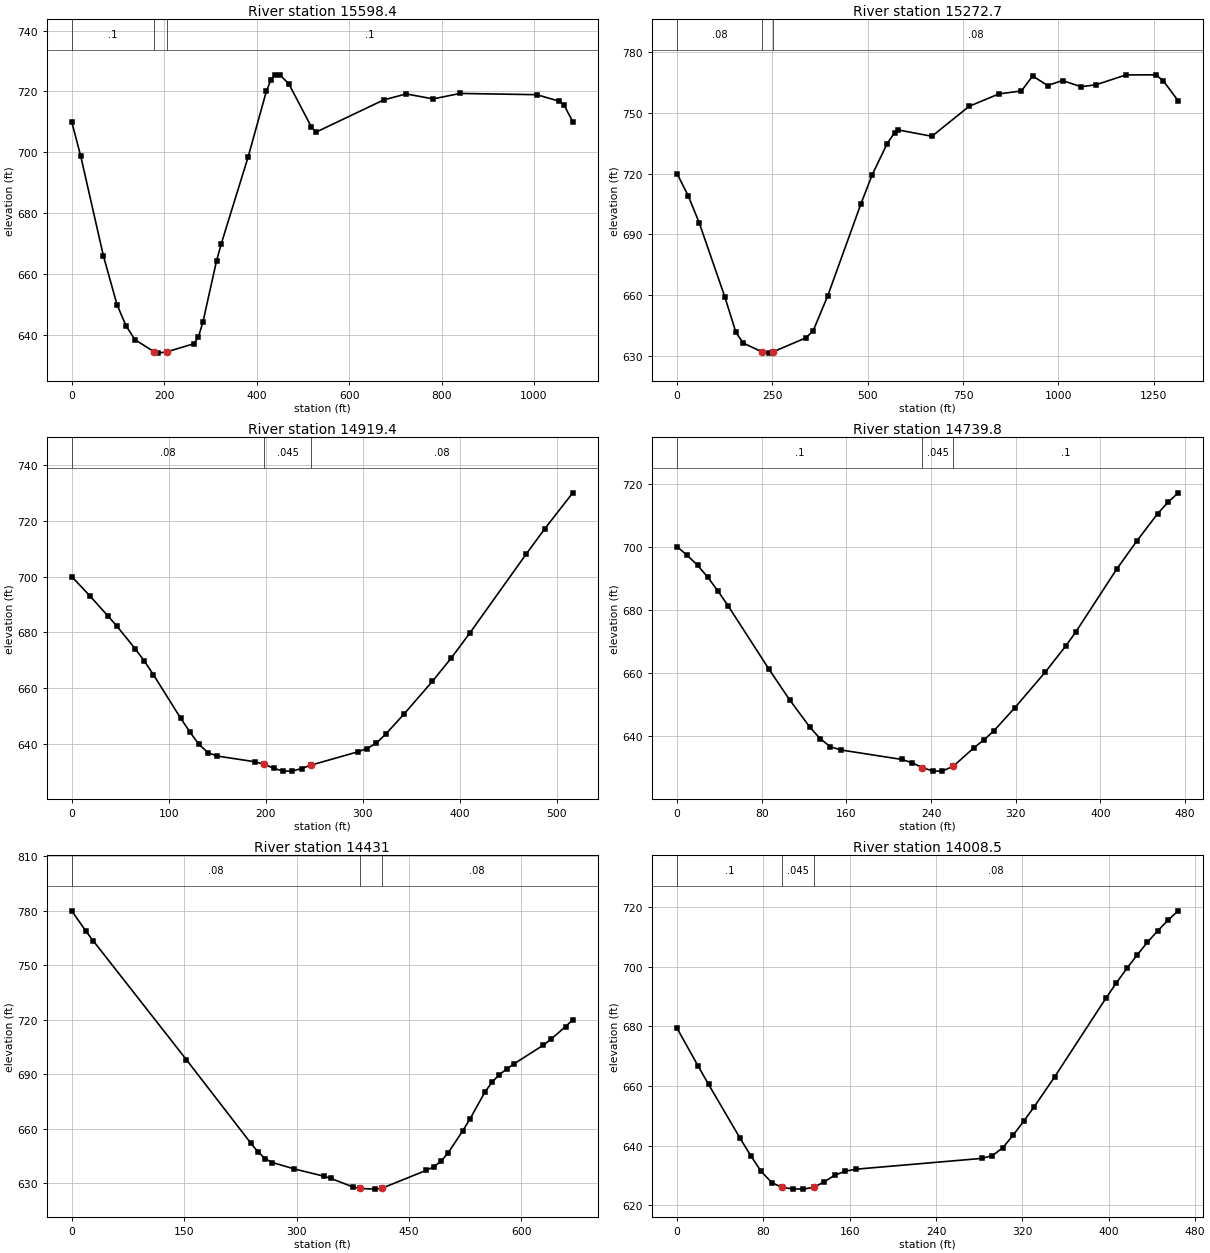
Type RM Length L Ch R = 1 ,15598.4 ,303,325.7,349.5
XS GIS Cut Line= 3
     1738424.989      561529.271     1738178.926      561870.901
     1737554.957      562095.074
#Sta/Elev= 30
       0     710    19.6  698.64    68.5  665.93    97.9  649.91   117.5   642.9
   137.1  638.32   178.7  634.32     186  633.93   205.6  634.34   264.4  637.03
   274.2   639.3   283.9   644.2   313.3  664.27   323.1  669.68   381.9  698.56
     421     720   430.8   723.8   440.5  725.44   450.3  725.44   469.8  722.44
   518.5  708.31   528.3  706.58   674.5  717.16   723.3  719.16   781.8  717.53
   840.3  719.32    1006  718.91  1054.8  716.77  1064.5  715.65    1084  710.01
#Mann= 3 , 0 , 0
       0      .1       0   178.7    .045       0   205.6      .1       0
Bank Sta=178.7,205.6
XS Rating Curve= 0 ,0
Exp/Cntr=0.3,0.1

Type RM Length L Ch R = 1 ,15272.7 ,345.7,353.3,360.8
XS GIS Cut Line= 3
     1738386.383      561409.992     1737933.657      561396.408
     1737095.732      561593.889
#Sta/Elev= 30
       0     720    28.9  709.23    57.8  695.88   125.3  659.14   154.2  641.66
   173.5  636.36   221.6  632.13   240.9   631.4   250.6  631.96   337.3  638.91
   356.6  642.34   395.1  659.75   482.3  705.26   511.6  719.49   550.8  734.84
   570.3  740.27   580.1  741.61   668.2  738.49     766  753.33   844.2  759.42
   902.9  760.89   932.3  768.28   971.4  763.56  1010.6  766.03  1059.5  762.95
  1098.6  763.94  1176.8   768.8  1255.1  768.84  1274.7  765.93  1313.8     756
#Mann= 3 , 0 , 0
       0     .08       0   221.6    .045       0   250.6     .08       0
Bank Sta=221.6,250.6
XS Rating Curve= 0 ,0
Exp/Cntr=0.3,0.1

Type RM Length L Ch R = 1 ,14919.4 ,177.9,179.6,181.1
XS GIS Cut Line= 3
     1738410.197      561158.981     1738286.871      561115.039
     1737929.094       560970.85
#Sta/Elev= 30
       0     700    18.7   693.1    37.4  685.87    46.8  682.15    65.5  674.14
    74.8  669.77    84.2  664.89   112.2  649.36   121.6  644.47   130.9  640.01
   140.6  636.92   150.2  635.72   188.8  633.69   198.4  632.77   208.1  631.41
   217.7  630.33   227.4  630.35   237.1  631.26   246.6  632.47   294.9  637.23
   304.5  638.43   314.2  640.41   323.8  643.57   343.1  650.94     372  662.51
   391.3  670.79   410.6  679.82   468.4  707.94   487.7  717.08   516.7  729.99
#Mann= 3 , 0 , 0
       0     .08       0   198.4    .045       0   246.6     .08       0
Bank Sta=198.4,246.6
XS Rating Curve= 0 ,0
Exp/Cntr=0.3,0.1

Type RM Length L Ch R = 1 ,14739.8 ,323.2,308.8,294.5
XS GIS Cut Line= 2
     1738484.044      561022.095     1738057.877      560815.836
#Sta/Elev= 30
       0     700     9.7  697.23    19.3  694.13      29  690.33    38.6  685.96
    48.3  681.24      87  661.12   106.3  651.53   125.6  642.79   135.3  639.17
   144.9  636.65   154.6  635.63   212.6  632.61   222.2  631.52   231.9  630.04
   241.6  628.95   250.4  628.92   260.9  630.43   280.2  636.24   289.9  638.79
   299.5  641.73   318.9  648.89   347.8  660.23   367.2  668.52   376.8     673
   415.5  692.93   434.8  701.96   454.1  710.45   463.8  714.03   473.5  717.06
#Mann= 3 , 0 , 0
       0      .1       0   231.9    .045       0   260.9      .1       0
Bank Sta=231.9,260.9
XS Rating Curve= 0 ,0
Exp/Cntr=0.3,0.1

Type RM Length L Ch R = 1 ,14431   ,447.2,422.5,397.8
XS GIS Cut Line= 3
     1738777.512       560522.36     1738522.382      560631.403
     1738136.349      560694.698
#Sta/Elev= 30
       0  779.98    19.1  768.68    28.7  763.46   153.1  697.92   239.2  651.86
   248.8  647.05   258.3  643.38   267.9   641.3     297  637.77   336.1  633.82
   345.9  632.54   375.2  627.85     385  627.02   404.6  626.65   413.8  627.14
     473  636.98   482.8  638.88   492.6  641.91   502.4  646.72     522   658.9
   531.7   665.5   551.3  680.08   561.1  685.75   570.8  689.76   580.6   692.9
   590.4  695.73   629.5  706.03   639.3  709.18   658.9  716.17   668.6  719.94
#Mann= 3 , 0 , 0
       0     .08       0     385    .045       0   413.8     .08       0
Bank Sta=385,413.8
XS Rating Curve= 0 ,0
Exp/Cntr=0.3,0.1

Type RM Length L Ch R = 1 ,14008.5 ,503.1,490.2,486.7
XS GIS Cut Line= 3
     1738274.545      560228.565     1738172.301      560533.298
     1738107.367      560660.534
#Sta/Elev= 30
       0  679.32    19.5  666.66    29.2  660.49    58.4  642.43    68.2  636.63
    77.9  631.32    87.7  627.58    97.4  625.94   107.1  625.47   116.9  625.38
   126.6  625.98   136.4  627.83   146.1  630.05   155.8  631.37   165.6  632.06
   282.5  635.69   292.2  636.62     302  639.32   311.7  643.62   321.4  648.26
     331  653.04     350   663.1   397.6  689.54   407.1  694.55   416.7  699.39
   426.2  703.84   435.7  708.12   445.2  711.92   454.8  715.54   464.3  718.71
#Mann= 3 , 0 , 0
       0      .1       0    97.4    .045       0   126.6     .08       0
Bank Sta=97.4,126.6
XS Rating Curve= 0 ,0
Exp/Cntr=0.3,0.1