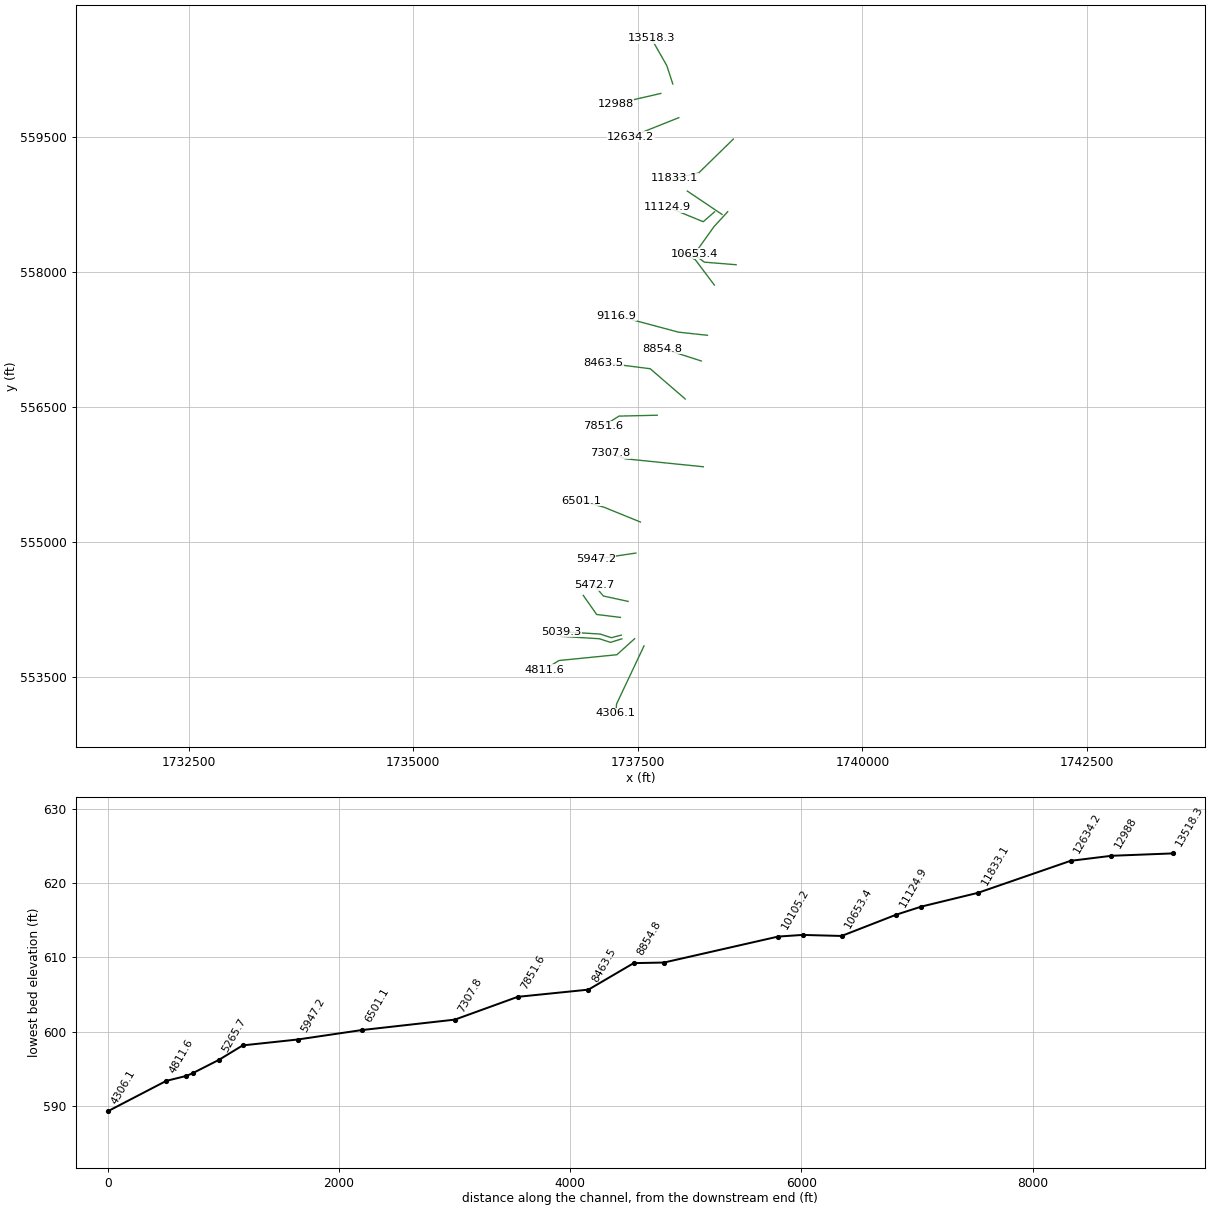
HEC-RAS study ManilaCr.prj: ManilaCr

--- ManilaCr.g01 (geometry) --- (continued)

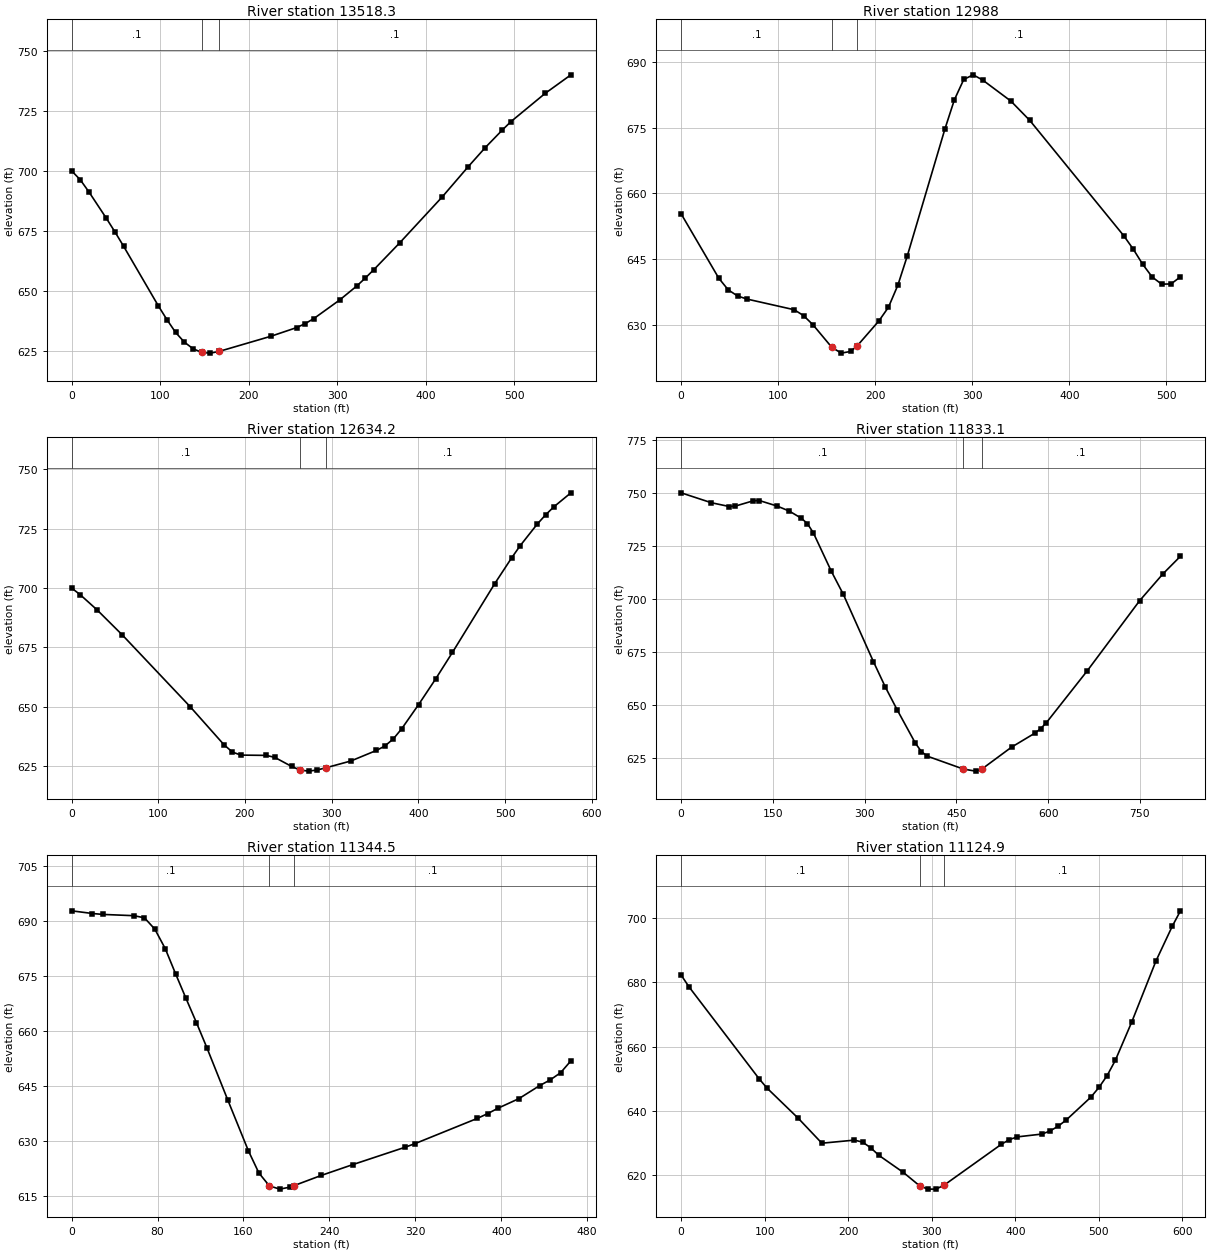
Type RM Length L Ch R = 1 ,13518.3 ,495.6,530.2,563
XS GIS Cut Line= 3
     1737889.216      560095.376     1737822.211      560300.175
     1737649.544      560602.907
#Sta/Elev= 30
       0  699.99     9.8  696.23    19.6  691.17    39.2  680.22      49  674.49
    58.8  668.49      98  643.67   107.7  637.93   117.5  632.61   127.3   628.6
   137.1  625.84   146.9   624.3   156.7     624   166.5   624.7   225.2  631.04
   254.2  634.65   263.9  636.31   273.6   638.4   302.6   646.1     322  651.95
   331.6  655.24   341.3  658.76   370.4  669.88   418.8  689.18   447.8  701.63
   467.2  709.65   486.6  717.03   496.2  720.48     535  732.29     564     740
#Mann= 3 , 0 , 0
       0      .1       0   146.9    .045       0   166.5      .1       0
Bank Sta=146.9,166.5
XS Rating Curve= 0 ,0
Exp/Cntr=0.3,0.1

Type RM Length L Ch R = 1 ,12988   ,350.5,353.9,357.2
XS GIS Cut Line= 2
     1737755.751      559989.746     1737254.315      559874.662
#Sta/Elev= 30
       0  655.35    38.8  640.71    48.5  638.07    58.2  636.67      68  635.97
   116.5  633.55   126.2   632.2   135.9  630.11   155.3  624.98     165  623.68
   174.7  624.07   181.6  625.39   203.8  631.02   213.6  634.12   223.3  639.14
     233  645.78   271.8  674.68   281.5  681.29   291.2  685.94   300.9  686.99
   310.6  685.82   339.8  681.01   359.2  676.63   456.2  650.35   465.9  647.32
   475.6  643.89   485.4  640.99   495.1  639.37   504.8  639.42   514.5  641.04
#Mann= 3 , 0 , 0
       0      .1       0   155.3    .045       0   181.6      .1       0
Bank Sta=155.3,181.6
XS Rating Curve= 0 ,0
Exp/Cntr=0.3,0.1

Type RM Length L Ch R = 1 ,12634.2 ,790.1,801.1,810.8
XS GIS Cut Line= 2
     1737955.965      559720.498     1737421.054      559506.836
#Sta/Elev= 30
       0  699.96     9.8   697.2    29.3  690.81    58.6   680.2   136.7  650.11
   175.7  634.12   185.5     631   195.3  629.74   224.5  629.62   234.3  628.79
   253.8  624.97   263.6  623.44   273.4     623   283.1  623.46   292.9  624.36
   322.2  627.27   351.5  631.68   361.2  633.52     371   636.5   380.8  640.82
   400.3  650.98   419.8  661.67   439.3  672.89   488.1  701.81   507.7   712.7
   517.4  717.74     537  726.78   546.7  730.71   556.5  734.17     576     740
#Mann= 3 , 0 , 0
       0      .1       0   263.6    .045       0   292.9      .1       0
Bank Sta=263.6,292.9
XS Rating Curve= 0 ,0
Exp/Cntr=0.3,0.1

Type RM Length L Ch R = 1 ,11833.1 ,518.7,488.6,457.2
XS GIS Cut Line= 3
     1738563.306      559481.845     1738176.666      559104.587
     1737907.216      559043.913
#Sta/Elev= 30
       0   749.9    49.1  745.25    78.6  743.45    88.4  743.63   117.9  746.15
   127.7  746.28   157.2  743.63   176.8  741.29   196.4  737.93   206.3  735.43
   216.1  731.05   245.5  712.93   265.2     702   314.3  670.34   333.9   658.3
   353.6  647.37     383  631.85   392.9  627.86   402.7  625.72   461.6  619.65
   481.3  618.69   491.1  619.54   540.2  629.99   578.3  636.58   587.8  638.72
   597.3  641.58     664  665.98   749.7  699.06   787.8   711.7   816.4     720
#Mann= 3 , 0 , 0
       0      .1       0   461.6    .045       0   491.1      .1       0
Bank Sta=461.6,491.1
XS Rating Curve= 0 ,0
Exp/Cntr=0.3,0.1

Type RM Length L Ch R = 1 ,11344.5 ,214.1,219.6,226.9
XS GIS Cut Line= 2
     1738437.458      558643.925     1738051.661      558903.244
#Sta/Elev= 30
       0   692.8    19.4  692.07      29  691.82    58.1  691.47    67.8  690.89
    77.5  687.78    87.2  682.45    96.8   675.6   106.5  668.88   116.2  662.28
   125.9  655.45   145.3  641.22   164.6  627.27   174.3  621.26     184  617.75
   193.7  616.84   203.4  617.39   206.8  617.77   232.4  620.58   261.5  623.51
   309.9  628.22   319.6  629.25   377.7  636.15   387.4  637.46   397.1  638.95
   416.4  641.54   435.8  645.11   445.5  646.65   455.2  648.61   464.8  651.86
#Mann= 3 , 0 , 0
       0      .1       0     184    .045       0   206.8      .1       0
Bank Sta=184,206.8
XS Rating Curve= 0 ,0
Exp/Cntr=0.3,0.1

Type RM Length L Ch R = 1 ,11124.9 ,441.4,471.5,499.4
XS GIS Cut Line= 3
     1738355.274      558673.289     1738228.139      558562.836
     1737830.944      558725.396
#Sta/Elev= 30
       0  682.19     9.4  678.54    93.6   649.9   102.9  647.08   140.3   637.7
   168.4     630   207.4  630.96   217.2  630.33   226.9  628.57   236.7  626.22
     266  620.91   285.5  616.75   295.2  615.74     305  615.74   314.7  616.97
     383  629.62   392.8  631.12   402.5  631.97   431.8  632.84   441.5  633.79
   451.3   635.3     461  637.23   490.3  644.28     500   647.3   509.8  650.98
   519.6   655.7   539.1  667.51   568.3   686.6   587.8  697.37   597.6  702.16
#Mann= 3 , 0 , 0
       0      .1       0   285.5    .045       0   314.7      .1       0
Bank Sta=285.5,314.7
XS Rating Curve= 0 ,0
Exp/Cntr=0.3,0.1

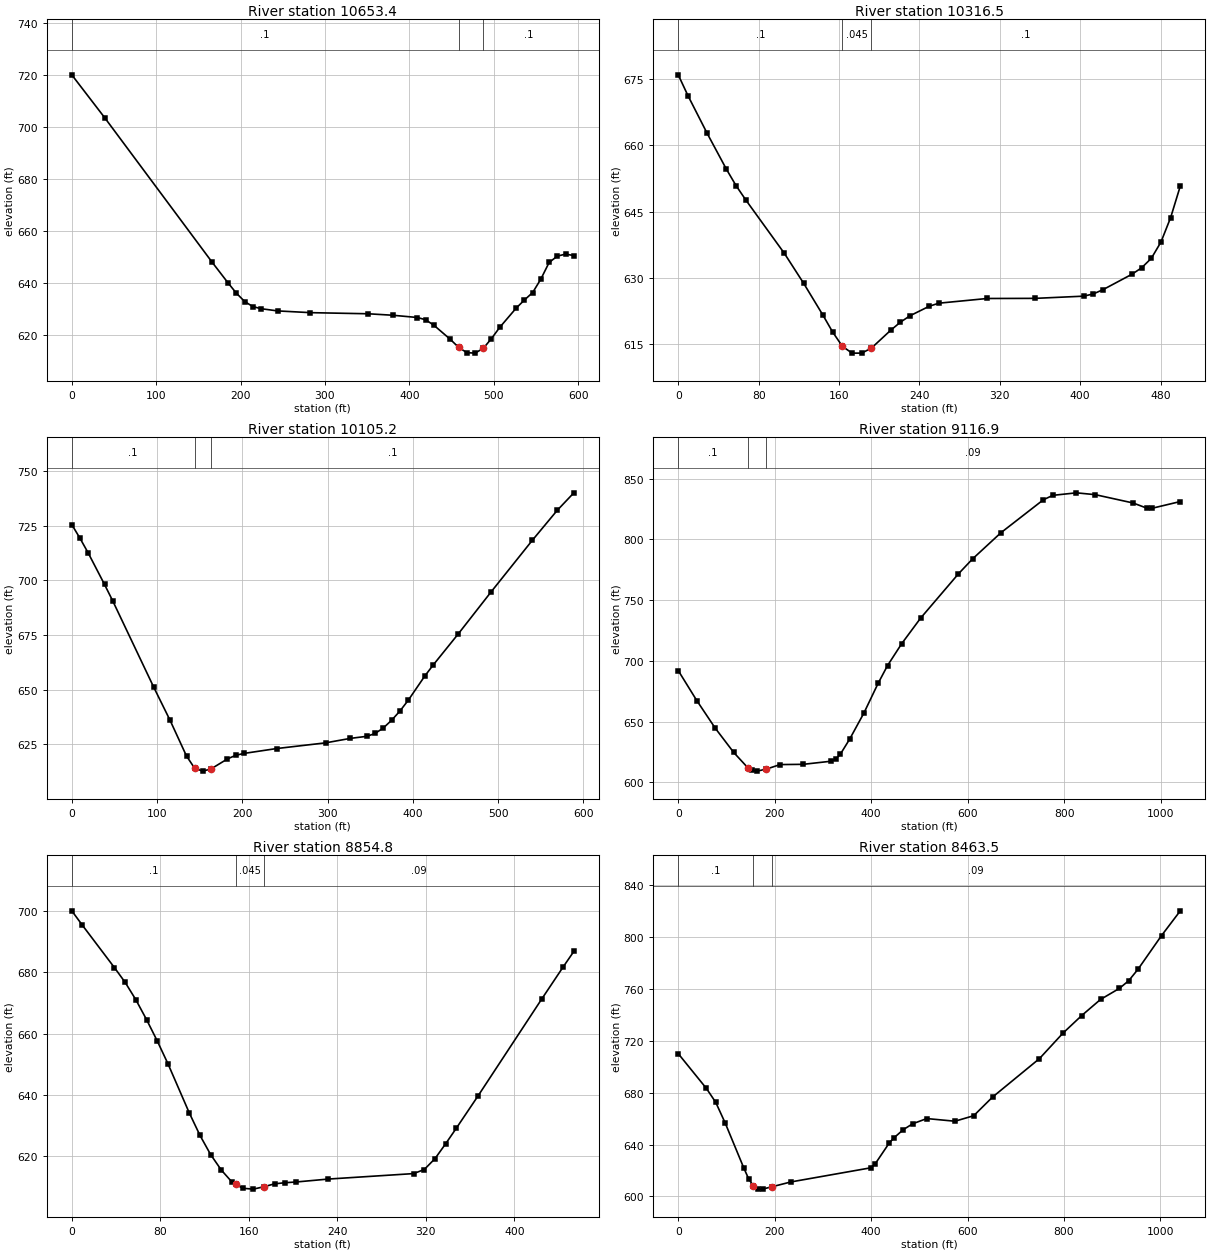
Type RM Length L Ch R = 1 ,10653.4 ,360.9,336.9,313.5
XS GIS Cut Line= 3
     1738500.634      558673.777     1738348.571      558508.777
     1738133.177      558207.243
#Sta/Elev= 30
       0     720      39   703.5   165.8   648.1   185.4  639.83   195.1  635.95
   204.9  632.75   214.6  630.79   224.4  629.98   243.9  629.13   282.9  628.46
   351.2  628.03   380.4  627.46   409.7  626.59   419.4  625.71   429.2   623.6
   448.7  618.16   458.4  615.11   468.2  613.06   477.9  612.88   487.7  614.72
   497.4  618.49   507.2  622.81   526.7  630.22   536.4  633.32   546.2   636.2
   555.9  641.38   565.7  647.77   575.4  650.22   585.2  650.99     595  650.44
#Mann= 3 , 0 , 0
       0      .1       0   458.4    .045       0   487.7      .1       0
Bank Sta=458.4,487.7
XS Rating Curve= 0 ,0
Exp/Cntr=0.3,0.1

Type RM Length L Ch R = 1 ,10316.5 ,231.1,211.3,190.8
XS GIS Cut Line= 3
     1738594.671      558084.141     1738240.402      558112.988
     1738125.347      558199.811
#Sta/Elev= 30
       0  675.98     9.6   671.3    28.8  662.73      48   654.6    57.6  650.89
    67.2  647.68   105.7  635.56   124.9  628.78   144.1  621.57   153.7  617.77
   163.3  614.58   172.9  613.02   182.5  613.02   192.1  614.13   211.3  618.17
     221  620.01   230.6  621.47   249.8  623.63   259.4  624.32   307.4  625.38
   355.4  625.41   403.5  625.91   413.1  626.42   422.7  627.38   451.5  630.87
   461.1  632.32   470.8  634.48   480.4  638.18     490   643.7   499.6  650.83
#Mann= 3 , 0 , 0
       0      .1       0   163.3    .045       0   192.1      .1       0
Bank Sta=163.3,192.1
XS Rating Curve= 0 ,0
Exp/Cntr=0.3,0.1

Type RM Length L Ch R = 1 ,10105.2 ,968.9,988.3,1006.7
XS GIS Cut Line= 3
     1738351.991      557858.137     1738138.037      558142.282
     1737926.584      558240.707
#Sta/Elev= 30
       0  725.49     9.6  719.26    19.2  712.57    38.4  698.13    48.1  690.56
    96.1  651.19   115.4  635.94   134.6  619.68   144.2  614.08   153.8   612.8
   163.4  613.82   182.6  618.38   192.3  620.03   201.9  620.89   240.3  623.12
     298  625.74   326.8  627.77   346.1  628.71   355.7     630   365.4  632.51
   375.1  636.04   384.8  640.21   394.6  645.16     414  656.22   423.7   661.2
   452.9  675.31   491.7  694.65   540.3  718.35   569.5  732.04   588.9     740
#Mann= 3 , 0 , 0
       0      .1       0   144.2    .045       0   163.4      .1       0
Bank Sta=144.2,163.4
XS Rating Curve= 0 ,0
Exp/Cntr=0.3,0.1

Type RM Length L Ch R = 1 ,9116.9  ,266.8,262.2,257.6
XS GIS Cut Line= 3
     1738275.189      557299.175     1737950.871      557334.525
     1737260.559      557519.427
#Sta/Elev= 30
       0  692.06    38.4  667.42    76.8  644.61   115.1  624.64   143.9  612.24
   153.5  609.82   163.1   609.3   182.3  610.91   211.1  614.69   259.1   614.9
   316.6  617.44   326.2  619.15     336  623.16   355.6  635.77     385  657.17
   414.4  681.57   433.9  696.18   463.3  714.21   502.4  735.18   580.8  771.62
   610.1  783.91   668.9  805.46     757  832.62   776.6  836.26   825.5  838.33
   864.7  836.81     943  829.97   972.4  825.58   982.2  825.61  1040.9  831.16
#Mann= 3 , 0 , 0
       0      .1       0   143.9    .045       0   182.3     .09       0
Bank Sta=143.9,182.3
XS Rating Curve= 0 ,0
Exp/Cntr=0.3,0.1

Type RM Length L Ch R = 1 ,8854.8  ,400.4,391.2,382.1
XS GIS Cut Line= 2
     1738207.062      557013.333     1737775.073      557152.233
#Sta/Elev= 30
       0  700.03     9.6  695.33    38.6  681.48    48.3  676.66    57.9  671.03
    67.6  664.53    77.2  657.62    86.9  650.16   106.2   634.1   115.9  626.74
   125.5   620.5   135.2  615.43   144.8  611.53   148.3   610.8   154.5   609.5
   164.1  609.22   173.8  610.01   183.4  610.96   193.1  611.32   202.8  611.55
   231.7   612.5     309  614.29   318.6  615.62   328.3  619.17   337.9  624.01
   347.6  629.11   366.9  639.47   424.8  671.27   444.1   681.7   453.8  686.79
#Mann= 3 , 0 , 0
       0      .1       0   148.3    .045       0   173.8     .09       0
Bank Sta=148.3,173.8
XS Rating Curve= 0 ,0
Exp/Cntr=0.3,0.1

Type RM Length L Ch R = 1 ,8463.5  ,591.4,611.9,629.6
XS GIS Cut Line= 3
     1738027.851      556590.604     1737637.589      556927.358
     1737115.936       556993.37
#Sta/Elev= 30
       0     710    58.4  683.23    77.8  672.48    97.3  656.66   136.2  621.74
   145.9  613.72   155.6  608.15   165.3  605.74   174.9  605.65   194.5  607.48
   233.4  611.17   398.8  622.04   408.5  625.13   437.7  641.22   447.4  645.15
   466.8  651.48   486.3     656   515.5     660   573.9  657.95   612.8  662.19
   651.8  676.52   749.2  706.19   797.8  725.75   836.8  739.35   875.8  751.74
   914.7   760.2   934.2  766.14   953.6  775.02  1002.3  800.92  1041.3     820
#Mann= 3 , 0 , 0
       0      .1       0   155.6    .045       0   194.5     .09       0
Bank Sta=155.6,194.5
XS Rating Curve= 0 ,0
Exp/Cntr=0.3,0.1

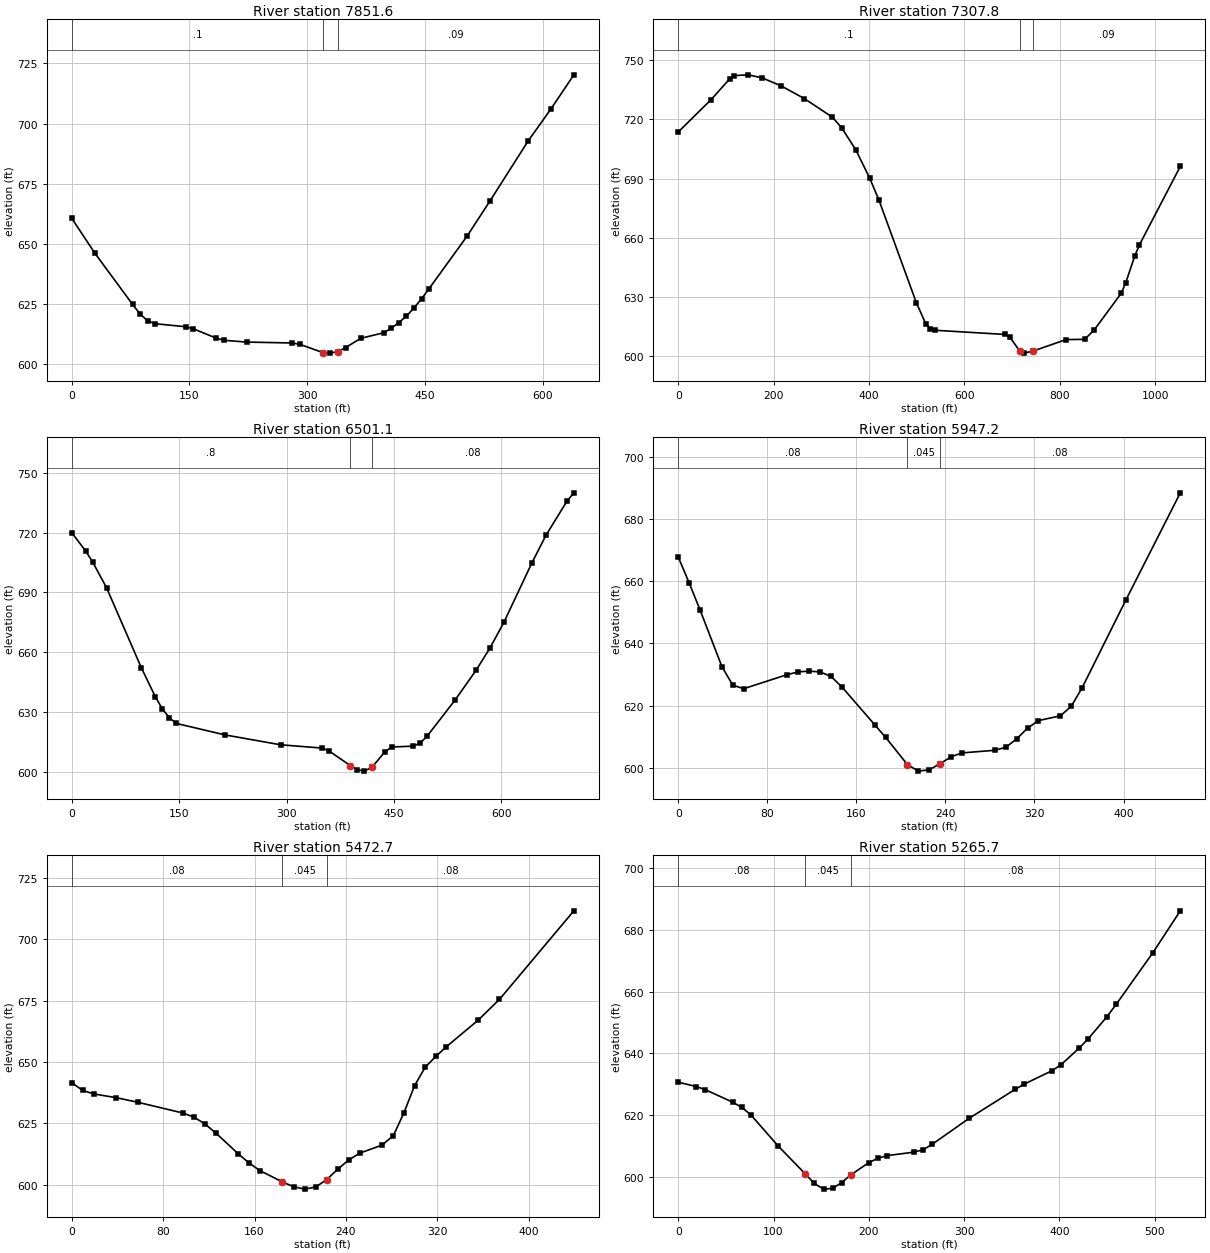
Type RM Length L Ch R = 1 ,7851.6  ,550,543.9,539.4
XS GIS Cut Line= 3
     1737716.607      556410.085     1737290.383       556400.16
     1737109.367      556287.175
#Sta/Elev= 30
       0  660.65    29.1  646.33    77.5  624.89    87.2  620.84    96.9  618.03
   106.6  616.88   145.3  615.63     155  614.77   184.1  610.89   193.8  610.01
   222.9  609.27     281  608.89   290.7  608.32   319.8  604.93   329.4  604.68
   339.1  605.33   348.8  606.97   368.2  610.83   397.3  613.12     407  614.96
   416.6  617.34   426.3     620     436  623.43   445.7  627.27   455.4  631.51
   503.9  653.36     533  667.94   581.5  692.78   610.6   706.1   639.7  720.23
#Mann= 3 , 0 , 0
       0      .1       0   319.8    .045       0   339.1     .09       0
Bank Sta=319.8,339.1
XS Rating Curve= 0 ,0
Exp/Cntr=0.3,0.1

Type RM Length L Ch R = 1 ,7307.8  ,824.9,806.7,799.2
XS GIS Cut Line= 3
     1738228.847      555836.787     1737361.479      555924.966
     1737190.838      555985.429
#Sta/Elev= 30
       0  713.63    68.6  729.96   107.8  740.51   117.6   742.2   146.9   742.6
   176.3  741.03   215.5  737.03   264.5  730.55   323.3  721.14   342.9  715.71
   372.2  704.66   401.6  690.24   421.2  678.97   499.6  626.98   519.2  616.44
     529  613.91   538.8  613.19   685.7  611.07   695.5  609.71   715.8  602.77
   724.9  601.61   744.5  602.68   813.1  608.46   852.2   608.6   871.8  613.19
     929  631.93   938.5  637.28   957.6  650.98   967.1  656.42  1052.9  696.22
#Mann= 3 , 0 , 0
       0      .1       0   715.8    .045       0   744.5     .09       0
Bank Sta=715.8,744.5
XS Rating Curve= 0 ,0
Exp/Cntr=0.3,0.1

Type RM Length L Ch R = 1 ,6501.1  ,541.6,553.9,565.6
XS GIS Cut Line= 3
     1737529.321      555221.661     1737123.949      555386.382
     1736869.874      555457.127
#Sta/Elev= 30
       0     720    19.4  710.78    29.2  705.23    48.6   692.3    97.2  652.11
   116.7  637.57   126.4  631.52   136.1  627.11   145.8  624.18   213.9   618.4
   291.7  613.43     350  611.77   359.8  610.22   388.9  603.02   398.7  600.92
   408.4   600.2   419.3   602.1   437.6     610   447.3  612.32   476.6  612.75
   486.4  614.19   496.2   617.7   535.2  635.82   564.6   650.8   584.1  662.01
   603.6  674.97   642.7  704.79   662.2  718.58   691.5  735.71   701.3     740
#Mann= 3 , 0 , 0
       0      .8       0   388.9    .045       0   419.3     .08       0
Bank Sta=388.9,419.3
XS Rating Curve= 0 ,0
Exp/Cntr=0.3,0.1

Type RM Length L Ch R = 1 ,5947.2  ,482.6,474.4,466.3
XS GIS Cut Line= 2
     1737478.561      554876.711     1737032.485      554810.085
#Sta/Elev= 30
       0  667.78     9.8  659.44    19.6  650.74    39.2  632.56      49  626.56
    58.8  625.43      98  629.97   107.8  630.84   117.7  631.08   127.5  630.82
   137.3  629.36   147.1  625.97   176.5  613.83   186.3  609.78   205.9  601.02
   215.7  598.93   225.5  599.36   235.3  601.34   245.1  603.53   254.9  604.79
   284.3  605.63   294.2  606.58     304  609.28   313.8  612.76   323.6  615.18
   343.2   616.7     353  619.75   362.8  625.72     402  653.87     451   688.4
#Mann= 3 , 0 , 0
       0     .08       0   205.9    .045       0   235.3     .08       0
Bank Sta=205.9,235.3
XS Rating Curve= 0 ,0
Exp/Cntr=0.3,0.1

Type RM Length L Ch R = 1 ,5472.7  ,204.9,207.1,209.1
XS GIS Cut Line= 3
     1737391.035      554338.914     1737115.936      554398.904
     1737013.313      554519.062
#Sta/Elev= 30
       0  641.56     9.7  638.38    19.4  636.96    38.8  635.46    58.2  633.54
    97.1  629.21   106.8  627.55   116.5  624.78   126.2     621   145.6  612.63
   155.4  608.74     165  605.63   184.5  601.06   194.2  599.12   203.9  598.14
   213.6  599.01   223.3  602.06     233  606.34   242.7  610.11   252.4  612.86
   271.8  616.13   281.6     620   290.9  629.35   300.2  640.41   309.4  647.86
   318.7  652.27     328  656.23   355.9  667.11   374.5  675.57   439.6  711.68
#Mann= 3 , 0 , 0
       0     .08       0   184.5    .045       0   223.3     .08       0
Bank Sta=184.5,223.3
XS Rating Curve= 0 ,0
Exp/Cntr=0.3,0.1

Type RM Length L Ch R = 1 ,5265.7  ,231.8,226.3,220
XS GIS Cut Line= 3
     1737306.387      554160.907     1737041.554      554193.451
     1736891.758      554406.175
#Sta/Elev= 30
       0  630.72    19.1   629.3    28.6  628.28    57.2  624.25    66.7  622.59
    76.2  620.18   104.8  610.14   133.4  601.08   142.9     598   152.5  596.18
     162  596.42   171.5  598.29   181.1  600.77   200.1  604.76   209.6  606.15
   219.2     607   247.8  608.15   257.3  608.94   266.8  610.71   305.4  619.06
   353.6  628.41   363.2   630.1   392.1   634.4   401.7  636.34     421  641.78
   430.6  644.83   449.9  651.85   459.6  655.83   498.1  672.51     527  686.08
#Mann= 3 , 0 , 0
       0     .08       0   133.4    .045       0   181.1     .08       0
Bank Sta=133.4,181.1
XS Rating Curve= 0 ,0
Exp/Cntr=0.3,0.1

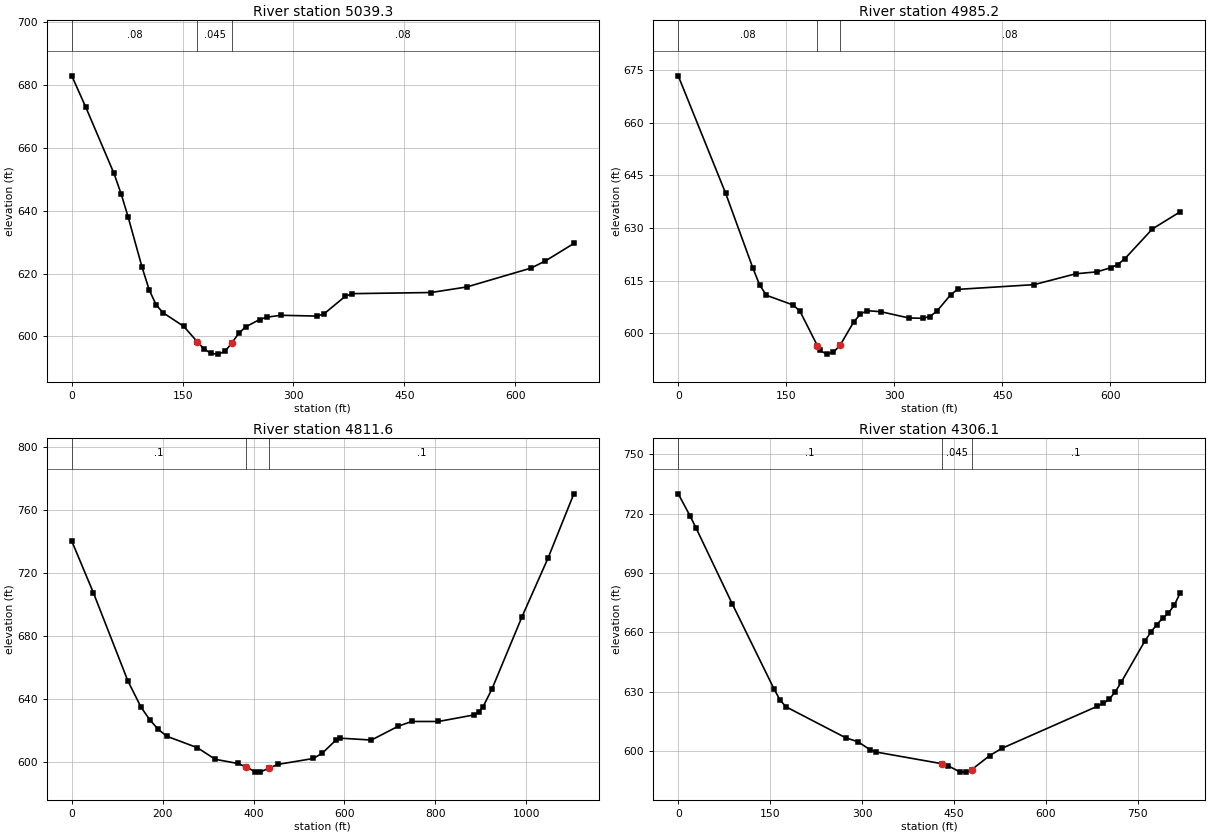
Type RM Length L Ch R = 1 ,5039.3  ,53.1,54.1,55.9
XS GIS Cut Line= 4
     1737315.083      553963.369     1737204.377      553935.034
     1737080.641      553975.402      1736646.49      554002.399
#Sta/Elev= 30
       0  682.88      19  672.89    57.1  651.86    66.7  645.42    76.2  638.05
    95.2  621.95   104.8   614.8   114.3     610   123.6  607.54   151.5  603.23
   170.1  598.24   179.4  595.96   188.6  594.59     198  594.39   207.2  595.23
   216.5  597.91   225.8  600.96   235.1  603.03   254.1  605.38   263.8  606.13
   283.1  606.74   331.4  606.49   341.1  607.15   370.1  612.78   379.8  613.62
   486.1  613.98   534.4  615.74   621.4  621.74   640.8  624.01   679.4  629.57
#Mann= 3 , 0 , 0
       0     .08       0   170.1    .045       0   216.5     .08       0
Bank Sta=170.1,216.5
XS Rating Curve= 0 ,0
Exp/Cntr=0.3,0.1

Type RM Length L Ch R = 1 ,4985.2  ,164.2,173.7,183.1
XS GIS Cut Line= 4
     1737321.598      553922.125     1737195.697      553882.935
     1737071.962      553923.303      1736637.81      553950.301
#Sta/Elev= 30
       0   673.3    65.9   639.8   103.6  618.56     113  613.73   122.4  610.79
   159.8     608     169  606.24   193.1  596.46   196.9  595.07   206.2  594.03
   215.5  594.58   224.8  596.58   243.4  603.13   252.7  605.39     262  606.41
   281.4  606.11     320  604.33   339.3  604.24     349  604.73   358.7  606.18
     378  610.89   387.7  612.47     494  613.82     552  616.92     581  617.46
   600.3  618.63     610  619.52   619.7  621.14   658.3   629.7     697  634.59
#Mann= 3 , 0 , 0
       0     .08       0   193.1    .045       0   224.8     .08       0
Bank Sta=193.1,224.8
XS Rating Curve= 0 ,0
Exp/Cntr=0.3,0.1

Type RM Length L Ch R = 1 ,4811.6  ,482.1,505.5,528.9
XS GIS Cut Line= 4
     1737464.378      553923.804     1737266.254      553745.365
     1736621.124      553680.943     1736460.502      553579.375
#Sta/Elev= 30
       0  740.01    47.6   707.2   123.8  651.02   152.4  634.63   171.4  626.67
   190.4  620.47   209.5   616.1   276.5  608.85   315.8   601.5   364.9  598.88
   384.5  596.63   404.2  593.42     414  593.36   433.6  595.83   453.3  598.24
   531.9  602.03   551.5  605.43     581  613.57   590.8  614.91   659.6  613.73
   718.5   622.5     748  625.51   806.9   625.5   885.5  629.67   895.3  631.33
   905.2  634.89   924.5  645.93     991  692.04    1048  729.07    1105     770
#Mann= 3 , 0 , 0
       0      .1       0   384.5    .045       0   433.6      .1       0
Bank Sta=384.5,433.6
XS Rating Curve= 0 ,0
Exp/Cntr=0.3,0.1

Type RM Length L Ch R = 1 ,4306.1  ,590,595.1,598
XS GIS Cut Line= 3
     1737568.691      553843.702     1737263.574      553198.503
     1737253.731       553093.08
#Sta/Elev= 30
       0     730    19.6  718.64    29.3  712.58      88  674.47   156.4  631.32
   166.2  625.69     176  622.29   273.8  606.57   293.3  604.64   312.9  600.65
   322.6  599.45   430.2  593.54     440  592.57   459.3  589.45   469.3  589.27
   479.1  590.54   508.4  597.62     528  601.25   684.4  622.61   694.2  624.04
   703.9  626.26   713.7     630   723.3  634.84   761.8  655.62   771.5  660.04
   781.1  663.88   790.7  667.06   800.3  669.71     810  673.85   819.6     680
#Mann= 3 , 0 , 0
       0      .1       0   430.2    .045       0   479.1      .1       0
Bank Sta=430.2,479.1
XS Rating Curve= 0 ,0
Exp/Cntr=0.3,0.1