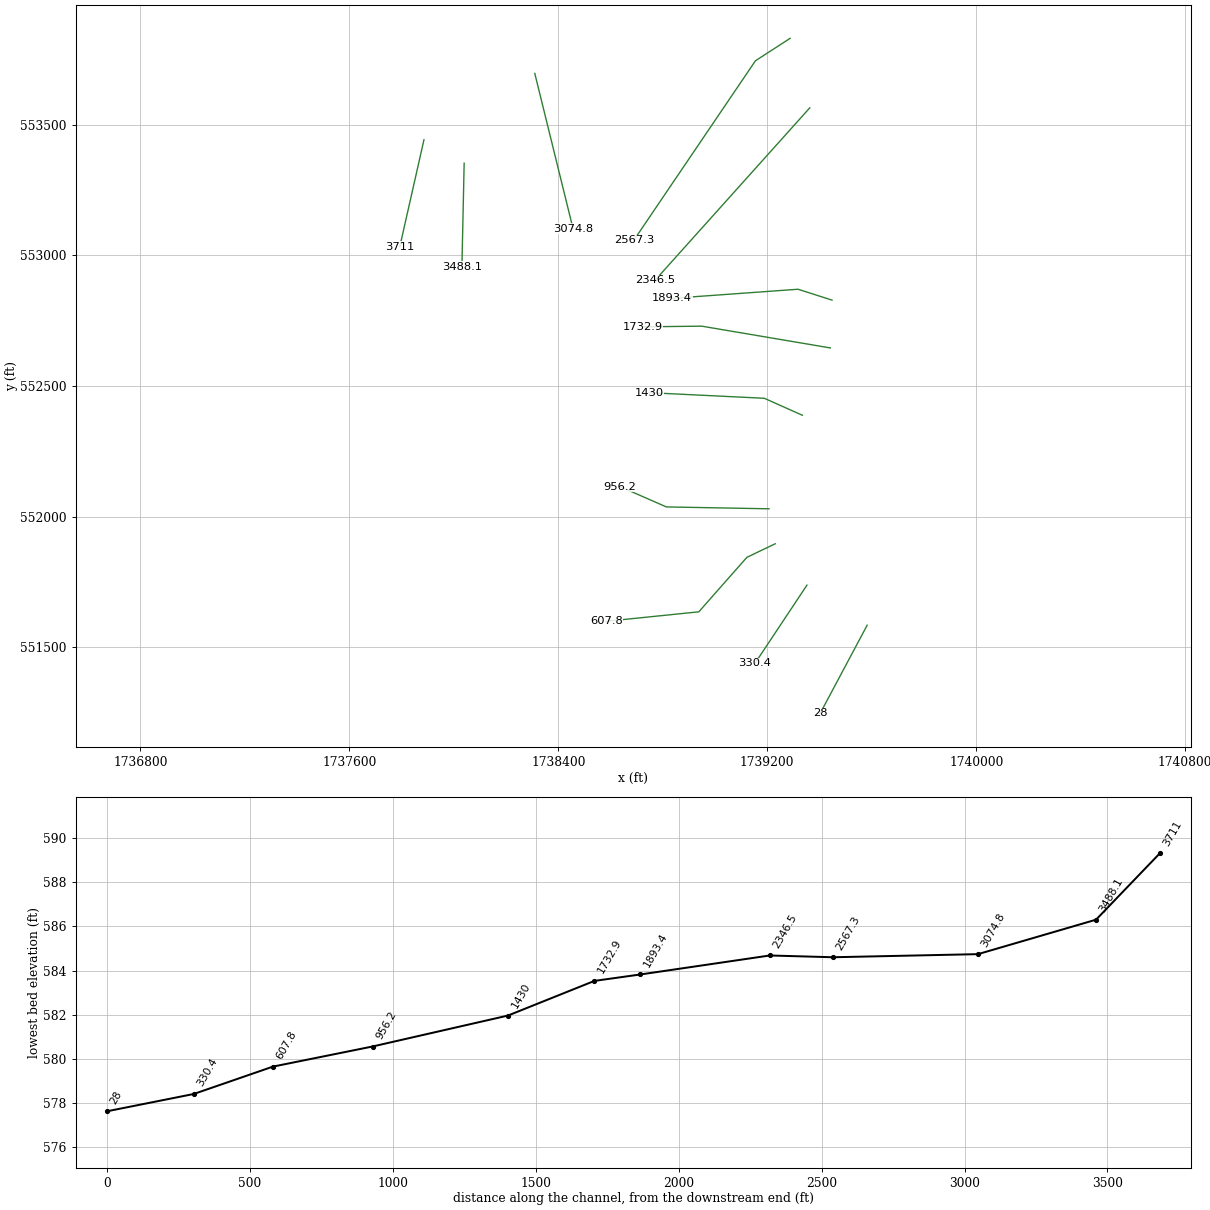
HEC-RAS study ManilaCr.prj: ManilaCr

--- ManilaCr.g01 (geometry) --- (continued)

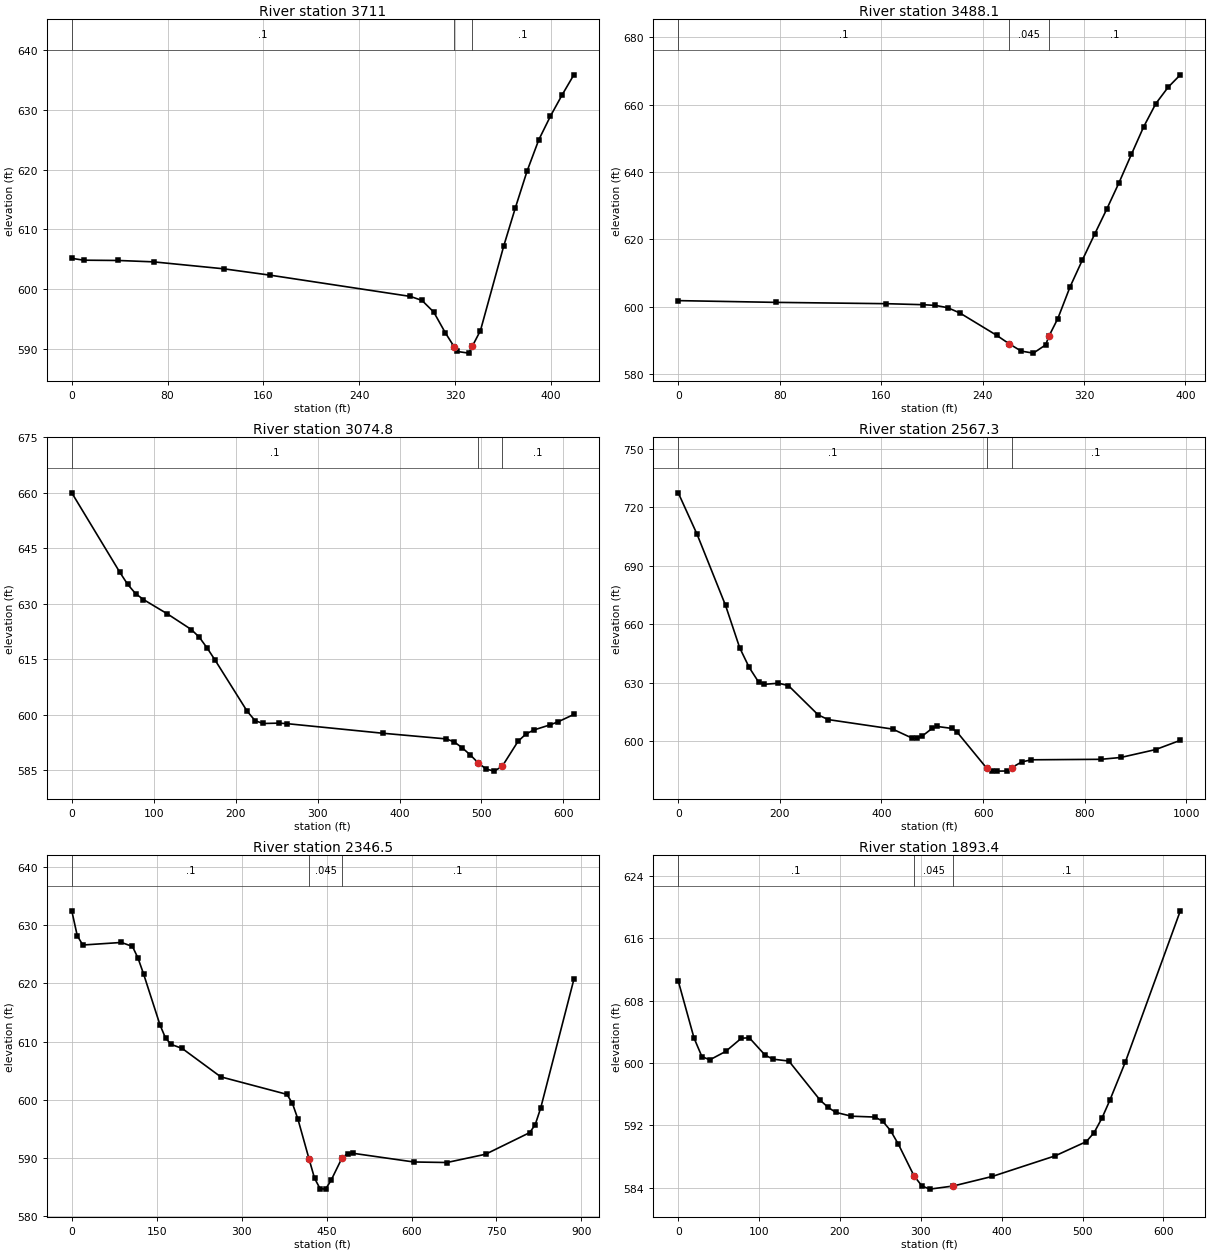
Type RM Length L Ch R = 1 ,3711    ,218.4,222.9,227.4
XS GIS Cut Line= 2
      1737885.59      553442.752     1737793.142      553033.776
#Sta/Elev= 22
       0  605.15     9.8  604.84      39  604.79    68.3  604.56   126.8   603.4
   165.8  602.33   282.8  598.78   292.5  598.11   302.3  596.16     312  592.69
   319.6  590.28   321.8  589.58   331.5   589.3   334.6  590.49   341.3  593.07
   360.8  607.25   370.5  613.62   380.3  619.77     390  624.96   399.8  628.94
   409.5  632.47   419.3  635.83
#Mann= 3 , 0 , 0
       0      .1       0   319.6    .045       0   334.6      .1       0
Bank Sta=319.6,334.6
XS Rating Curve= 0 ,0
Exp/Cntr=0.3,0.1

Type RM Length L Ch R = 1 ,3488.1  ,407,413.3,418.9
XS GIS Cut Line= 2
     1738039.502      553353.109     1738030.844      552957.164
#Sta/Elev= 24
       0  601.87    77.3  601.35   164.2  600.96   193.2  600.66   202.8  600.45
   212.5  599.78   222.2  598.19   251.2  591.57   260.8  589.12   270.5   586.9
   280.1   586.3   289.8  588.75  292.39  591.34   299.4  596.56   309.1  606.01
   318.8  613.95   328.4  621.55   338.1   629.1   347.7  636.88   357.4  645.23
   367.1  653.42   376.7   660.3   386.4  665.16     396  668.83
#Mann= 3 , 0 , 0
       0      .1       0   260.8    .045       0  292.39      .1       0
Bank Sta=260.8,292.39
XS Rating Curve= 0 ,0
Exp/Cntr=0.3,0.1

Type RM Length L Ch R = 1 ,3074.8  ,527.7,507.5,484.8
XS GIS Cut Line= 2
     1738309.893      553696.487     1738456.498      553101.591
#Sta/Elev= 30
       0     660    58.4   638.6    68.1  635.28    77.8  632.76    87.5  631.14
   116.7  627.26   145.9  623.03   155.6  620.96   165.3     618   175.1  614.69
     214  600.95   223.7  598.39   233.4  597.62   252.9  597.72   262.6  597.58
   379.3  594.99   457.1  593.45   466.8  592.62   476.5  591.04   486.3  589.13
     496  586.96   505.7   585.3   515.4  584.74   525.2  586.01   544.6   592.8
   554.3  594.79   564.1  595.88   583.5  597.24   593.2  598.05   612.7  600.07
#Mann= 3 , 0 , 0
       0      .1       0     496    .045       0   525.2      .1       0
Bank Sta=496,525.2
XS Rating Curve= 0 ,0
Exp/Cntr=0.3,0.1

Type RM Length L Ch R = 1 ,2567.3  ,222.9,220.8,220.2
XS GIS Cut Line= 3
     1739287.415      553831.017     1739154.571      553745.047
     1738689.009      553057.929
#Sta/Elev= 30
       0  727.32    37.2  705.98    93.1   669.6     121  647.84   139.6   637.8
   158.2  630.27     168  629.09   197.3  629.68   216.8  628.48   275.4  613.46
   294.9  611.04   421.9  606.17   460.9  601.46   470.7  601.47   480.5  602.64
     500  606.58   509.8  607.49     539   606.5   548.8  604.63   607.4  586.02
   617.2   584.7   626.9   584.6   646.5  584.67   656.2  586.34   675.8   589.3
   695.3  590.41     832  590.66     871   591.6   939.4  595.64   988.2  600.39
#Mann= 3 , 0 , 0
       0      .1       0   607.4    .045       0   656.2      .1       0
Bank Sta=607.4,656.2
XS Rating Curve= 0 ,0
Exp/Cntr=0.3,0.1

Type RM Length L Ch R = 1 ,2346.5  ,466.2,453.1,435.6
XS GIS Cut Line= 2
     1739362.778       553565.06     1738770.639      552905.113
#Sta/Elev= 30
       0  632.46     9.7  628.19    19.5  626.59    87.7  627.03   107.2  626.34
   116.9  624.36   126.7  621.66   155.9  612.85   165.6  610.62   175.4  609.53
   194.9  608.84   263.1  603.96     380  600.95   389.7   599.4   399.5  596.67
     419  589.87   428.7  586.56   438.5  584.76   448.2  584.68   457.9  586.18
   477.4  590.06   487.2  590.78   496.9  590.83   604.1  589.34   662.6  589.25
   730.8  590.67   808.7  594.38   818.4  595.73   828.2  598.62   886.7  620.67
#Mann= 3 , 0 , 0
       0      .1       0     419    .045       0   477.4      .1       0
Bank Sta=419,477.4
XS Rating Curve= 0 ,0
Exp/Cntr=0.3,0.1

Type RM Length L Ch R = 1 ,1893.4  ,171.2,160.5,154.1
XS GIS Cut Line= 3
     1739447.919      552828.746     1739317.671      552870.416
     1738834.898      552835.653
#Sta/Elev= 30
       0  610.51    19.5   603.2    29.3   600.8    39.1   600.4    58.6  601.47
    78.1  603.17    87.9  603.22   107.4     601   117.2  600.48   136.8  600.24
   175.5  595.22   185.2  594.31   194.8  593.66   214.2  593.17   243.2  593.06
   252.9  592.52   262.6  591.31   272.3  589.56   291.6  585.51   301.3  584.23
     311  583.82     340  584.22   388.4  585.45   465.9  588.08   504.6  589.91
   514.3  591.08     524  592.94   533.6   595.2     553  600.16   620.8   619.5
#Mann= 3 , 0 , 0
       0      .1       0   291.6    .045       0     340      .1       0
Bank Sta=291.6,340
XS Rating Curve= 0 ,0
Exp/Cntr=0.3,0.1

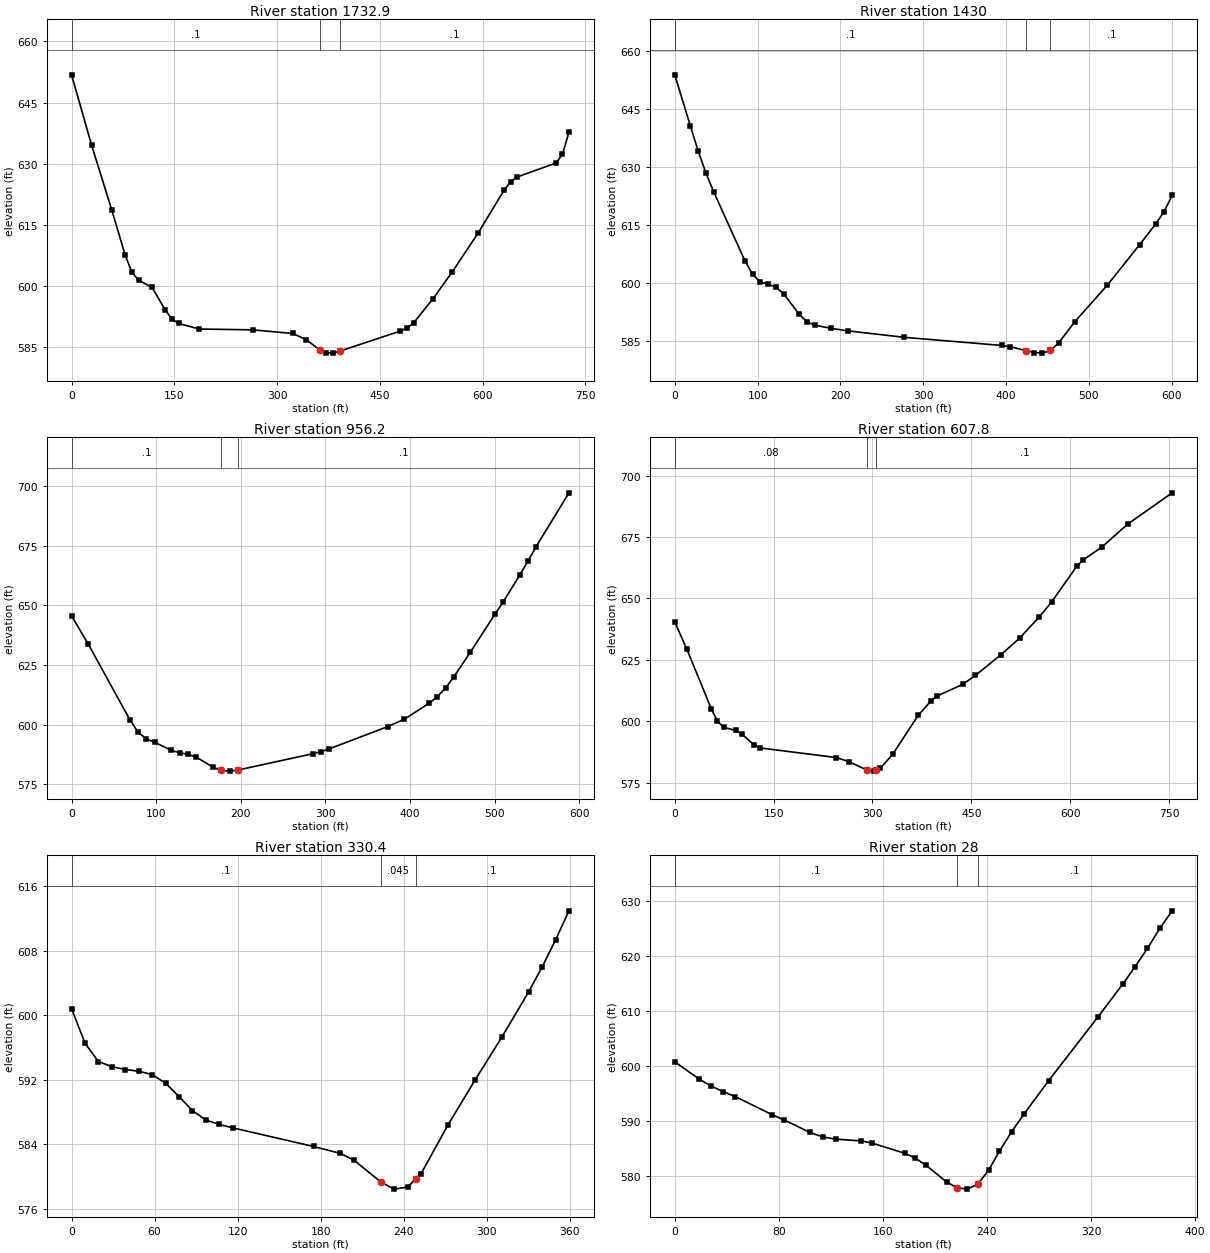
Type RM Length L Ch R = 1 ,1732.9  ,299.7,302.9,306
XS GIS Cut Line= 3
      1739441.18      552645.797     1738948.848      552729.122
     1738722.222      552726.503
#Sta/Elev= 30
       0  651.82    29.4  634.48    58.8  618.62    78.3  607.56    88.1  603.38
    97.9  601.43   117.5  599.64   137.1  594.03   146.9  591.83   156.6  590.81
     186  589.45   264.4  589.24   323.1  588.35   342.7   586.8   362.3  584.34
     372  583.62   381.8  583.53   391.6  584.02   479.8  588.94   489.5  589.67
   499.3  590.95   527.7   596.9     556  603.53   593.8  613.11   631.5  623.57
     641  625.64   650.4  626.75   707.1  630.18   716.5  632.31     726  637.75
#Mann= 3 , 0 , 0
       0      .1       0   362.3    .045       0   391.6      .1       0
Bank Sta=362.3,391.6
XS Rating Curve= 0 ,0
Exp/Cntr=0.3,0.1

Type RM Length L Ch R = 1 ,1430    ,473,473.8,474.6
XS GIS Cut Line= 3
     1739334.396      552387.904     1739188.517      552453.018
     1738748.091      552474.435
#Sta/Elev= 30
       0  653.73    18.8  640.54    28.2  634.15    37.6   628.4      47  623.57
    84.6  605.81      94  602.24   103.4   600.3   112.8  599.73   122.2  598.95
   131.6  597.23   150.4  591.94   159.8  590.01   169.6  589.14   189.2  588.34
   208.7  587.71   277.3  586.03   394.9  583.94   404.7  583.62   424.3  582.62
   434.1  582.12   443.9  581.96   453.7  582.64   463.5  584.58   483.1  590.06
   522.3  599.48   561.5  609.96   581.1  615.37   590.9  618.46   600.7  622.67
#Mann= 3 , 0 , 0
       0      .1       0   424.3    .045       0   453.7      .1       0
Bank Sta=424.3,453.7
XS Rating Curve= 0 ,0
Exp/Cntr=0.3,0.1

Type RM Length L Ch R = 1 ,956.2   ,328.3,348.4,368.2
XS GIS Cut Line= 3
     1739206.582      552029.894     1738813.438      552037.078
     1738635.431      552115.214
#Sta/Elev= 30
       0  645.67    19.7  633.86    68.8  602.16    78.6  596.87    88.5  594.02
    98.3  592.62     118  589.24   127.8  588.23   137.6  587.59   147.4  586.42
   167.1  582.22   176.9  580.84   186.8  580.56   196.6  581.02   285.1  587.86
   294.9  588.75   304.7  589.93   373.6  599.24   393.2  602.32   422.4  609.01
   432.1   611.8   441.8  615.38   451.5  620.02     471  630.33   500.1  646.33
   509.8  651.42   529.3  662.67     539  668.51   548.7  674.62   587.6  697.23
#Mann= 3 , 0 , 0
       0      .1       0   176.9    .045       0   196.6      .1       0
Bank Sta=176.9,196.6
XS Rating Curve= 0 ,0
Exp/Cntr=0.3,0.1

Type RM Length L Ch R = 1 ,607.8   ,274,277.4,280.3
XS GIS Cut Line= 4
     1739230.231      551896.006     1739121.696      551843.901
       1738937.9      551635.463      1738583.17      551599.178
#Sta/Elev= 30
       0  640.37    18.5  629.21    55.6  604.91    64.8  599.98    74.1  597.48
    92.6  596.23   101.9   594.7   120.4  590.33     130  589.08     245  585.19
   264.1  583.53   291.1  580.14   302.5  579.65   306.1  580.09     312   580.8
   331.2   586.7   369.5  602.41   388.7  608.22   398.3  610.27   436.8  614.98
   456.1  618.61   494.7     627   523.6   633.9   552.5  642.26   571.8  648.51
   610.3   663.2     620   665.7   648.9  671.09   687.4  680.29   754.9  693.01
#Mann= 3 , 0 , 0
       0     .08       0   291.1    .045       0   306.1      .1       0
Bank Sta=291.1,306.1
XS Rating Curve= 0 ,0
Exp/Cntr=0.3,0.1

Type RM Length L Ch R = 1 ,330.4   ,300.1,302.5,304.5
XS GIS Cut Line= 2
     1739351.803      551737.548     1739152.785      551438.144
#Sta/Elev= 28
       0  600.82     9.7  596.52    19.4  594.24    29.2   593.6    38.9  593.25
    48.6  593.04    58.3  592.62      68  591.54    77.7   589.9    87.4  588.14
    97.2  586.98   106.9  586.43   116.6  586.01   174.9   583.7   194.3  582.84
     204  582.02   223.5   579.3   233.2  578.41   242.9  578.67   248.6  579.64
   252.6  580.32   272.1  586.38   291.5  591.91   310.9  597.24   330.4   602.9
   340.1  605.97   349.8  609.33   359.5  612.94
#Mann= 3 , 0 , 0
       0      .1       0   223.5    .045       0   248.6      .1       0
Bank Sta=223.5,248.6
XS Rating Curve= 0 ,0
Exp/Cntr=0.3,0.1

Type RM Length L Ch R = 1 ,28      ,30.3,28,25.4
XS GIS Cut Line= 6
     1739582.309      551584.114     1739547.256      551518.365
     1739491.359      551413.518     1739476.694      551386.012
      1739464.92      551363.926     1739402.408      551246.671
#Sta/Elev= 30
       0  600.77    18.6  597.66    27.9  596.37    37.2  595.34    46.6  594.44
    74.5  591.19    84.3  590.18   103.9  587.93   113.7  587.12   123.6  586.72
   143.2   586.4   151.5  586.01   176.6  584.16     185  583.26   193.3  581.94
   208.9  578.94   216.7  577.92   224.5  577.63   232.8  578.48   241.2  581.06
   249.5  584.49     259  588.08   268.5   591.3   287.5  597.37   325.5  608.98
   344.4  614.91   353.9  618.07   363.4   621.4   372.9  625.05   382.4  628.22
#Mann= 3 , 0 , 0
       0      .1       0   216.7    .045       0   232.8      .1       0
Bank Sta=216.7,232.8
XS Rating Curve= 0 ,0
Exp/Cntr=0.3,0.1

Chan Stop Cuts=-1
Use User Specified Reach Order=0
Composite Channel Slope=5